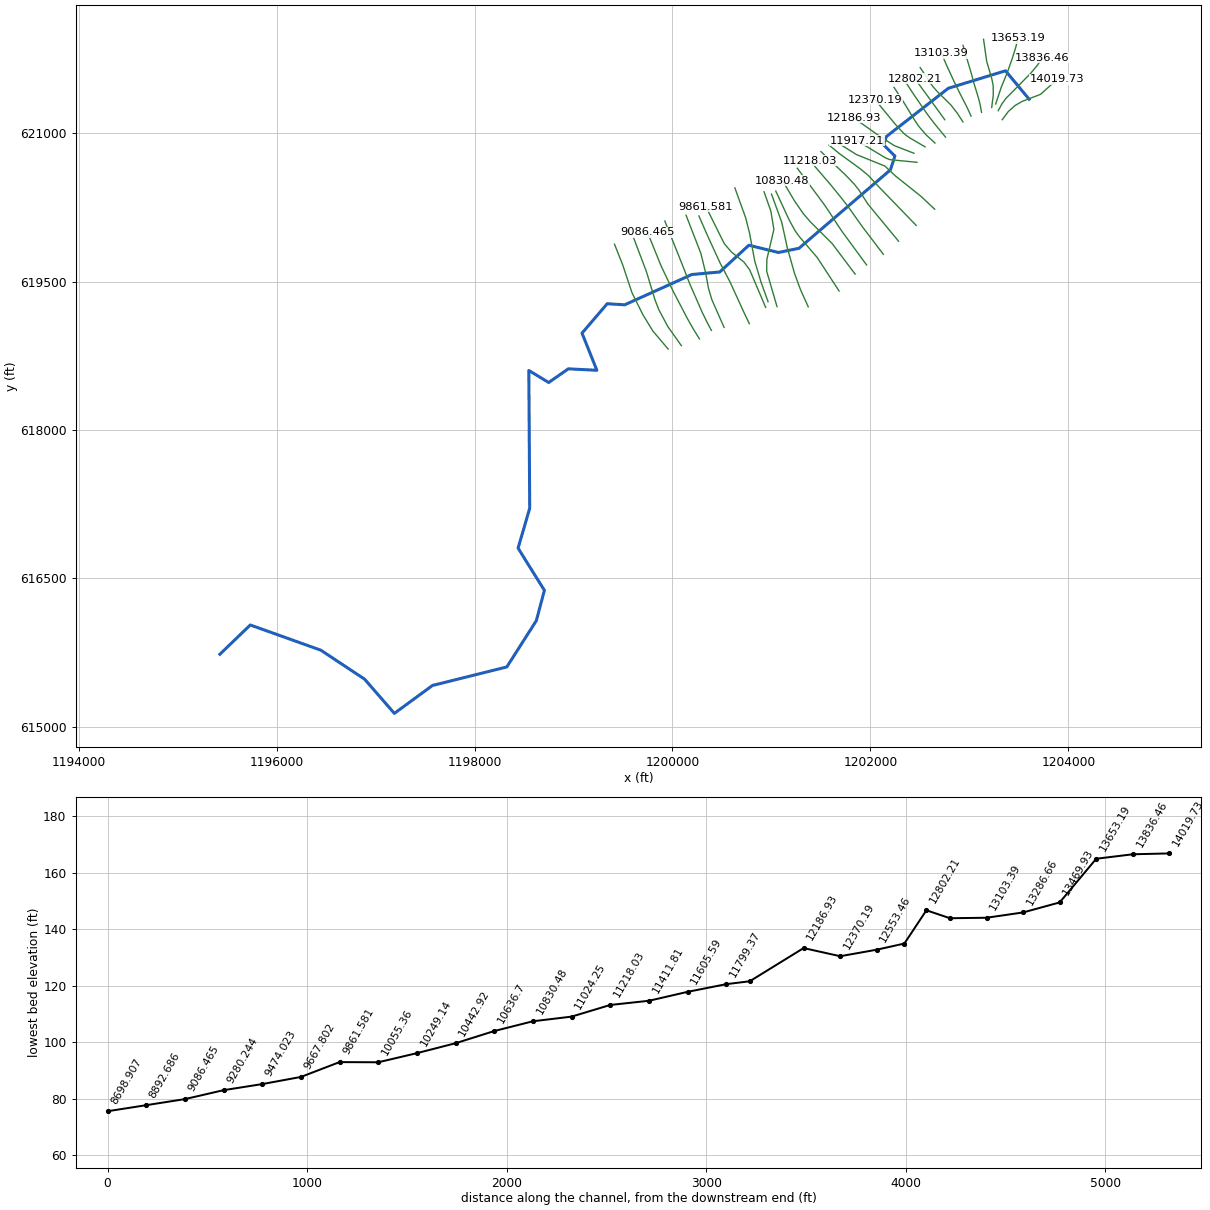
--- 128_ras.prj (project) ---

Proj Title=128
Current Plan=p01
Default Exp/Contr=0.3,0.1
English Units
Geom File=g01
Flow File=f01
Plan File=p01
Y Axis Title=Elevation
X Axis Title(PF)=Main Channel Distance
X Axis Title(XS)=Station
BEGIN DESCRIPTION:
RFD model 128 exported to HEC-RAS
END DESCRIPTION:

--- 128_ras.p01 (plan) ---

Plan Title=Plan 01
Program Version=4.10
Short Identifier=Plan 01
Geom File=g01
Flow File=f01
Subcritical Flow
Calc Critical at every XS
Secant Critical Depth

--- 128_ras.f01 (steady flow) ---

Flow Title=Flow 01
Program Version=5.01
Number of Profiles= 5
Profile Names=10yr,25yr,50yr,100yr,500yr
River Rch & RM=128,54,14019.73
 1429.47 2066.51  2573.5 3334.27 5017.54
River Rch & RM=128,54,13836.46
 1435.46 2076.44 2586.22 3352.83 5049.46
River Rch & RM=128,54,13653.19
 1436.98 2078.96 2589.45 3357.54 5057.58
River Rch & RM=128,54,13469.93
 1438.62 2081.67 2592.92 3362.61 5066.31
River Rch & RM=128,54,13286.66
  1577.1 2312.91 2889.76 3798.86 5824.26
River Rch & RM=128,54,13103.39
 1578.32 2314.96 2892.39 3802.75 5831.07
River Rch & RM=128,54,12920.13
 1580.04 2317.85  2896.1 3808.25 5840.71
River Rch & RM=128,54,12802.21
 1590.39 2335.27  2918.5 3841.41 5898.89
River Rch & RM=128,54,12691.68
 1591.59 2337.29  2921.1 3845.26 5905.64
River Rch & RM=128,54,12553.46
 1592.39 2338.63 2922.83 3847.82 5910.14
River Rch & RM=128,54,12370.19
 1595.08 2343.17 2928.66 3856.46  5925.3
River Rch & RM=128,54,12186.93
 1595.98 2344.67  2930.6 3859.33 5930.35
River Rch & RM=128,54,11917.21
 1616.57 2379.38 2975.25 3925.57 6046.82
River Rch & RM=128,54,11799.37
 1618.42 2382.51 2979.27 3931.54 6057.33
River Rch & RM=128,54,11605.59
 1627.44 2397.73 2998.86 3960.65 6108.62
River Rch & RM=128,54,11411.81
  1628.7 2399.85 3001.59  3964.7 6115.76
River Rch & RM=128,54,11218.03
 1676.62 2480.95    3106 4120.25 6390.77
River Rch & RM=128,54,11024.25
 1677.54 2482.51 3108.02 4123.26  6396.1
River Rch & RM=128,54,10830.48
 1679.84 2486.42 3113.05 4130.77 6409.42
River Rch & RM=128,54, 10636.7
  1681.4 2489.07 3116.46 4135.88 6418.47
River Rch & RM=128,54,10442.92
 1693.28 2509.23 3142.44  4174.7 6487.38
River Rch & RM=128,54,10249.14
 1698.54 2518.16 3153.96 4191.92 6517.97
River Rch & RM=128,54,10055.36
 1700.71 2521.85 3158.71 4199.02  6530.6
River Rch & RM=128,54,9861.581
 1702.15  2524.3 3161.87 4203.75 6539.01
River Rch & RM=128,54,9667.802
 1703.95 2527.37 3165.81 4209.66 6549.51
River Rch & RM=128,54,9474.023
 1704.76 2528.74 3167.59 4212.31 6554.23
River Rch & RM=128,54,9280.244
 1705.57 2530.12 3169.36 4214.97 6558.95
River Rch & RM=128,54,9086.465
 1724.91 2563.02 3211.78  4278.5 6672.07
River Rch & RM=128,54,8892.686
 1726.76 2566.18 3215.85 4284.61 6682.95
River Rch & RM=128,54,8698.907
 1730.28 2572.18 3223.58 4296.21 6703.64
River Rch & RM=128,54,8505.128
 1738.69 2586.51 3242.07 4323.94 6753.12
River Rch & RM=128,54, 8311.35
    1740 2588.74 3244.95 4328.26 6760.83
River Rch & RM=128,54, 8023.35
 1741.65 2591.56 3248.59 4333.73 6770.59
River Rch & RM=128,54,7626.304
 1744.61  2596.6 3255.09 4343.49 6788.03
River Rch & RM=128,54,7229.258
 1747.12 2600.89 3260.62  4351.8 6802.88
River Rch & RM=128,54,7030.736
 1747.64 2601.78 3261.77 4353.52 6805.94
River Rch & RM=128,54,6832.213
 1748.77  2603.7 3264.24 4357.24 6812.59
River Rch & RM=128,54,6435.167
 1749.98 2605.76 3266.91 4361.24 6819.75
River Rch & RM=128,54,6236.645
 1750.24 2606.21 3267.48  4362.1 6821.28
River Rch & RM=128,54,5936.645
 1755.67 2615.48 3279.43 4380.07  6853.4
River Rch & RM=128,54,5438.106
 1757.99 2619.44 3284.54 4387.75 6867.14
River Rch & RM=128,54,4939.568
 1858.55 2791.89 3507.25 4723.98  7471.8
River Rch & RM=128,54,4232.694
 1874.21 2818.86 3542.12 4776.87 7567.49
River Rch & RM=128,54,3721.908
 1903.49  2869.4 3607.48 4876.18 7747.58
River Rch & RM=128,54,3175.406
 1914.69 2888.74 3632.51 4914.27 7816.78
River Rch & RM=128,54,2780.943
 1916.72 2892.26 3637.05 4921.19 7829.36
Boundary for River Rch & Prof#=128,54,1
Up Type= 0
Dn Type= 2
Boundary for River Rch & Prof#=128,54,2
Up Type= 0
Dn Type= 2
Boundary for River Rch & Prof#=128,54,2
Up Type= 0
Dn Type= 2
Boundary for River Rch & Prof#=128,54,2
Up Type= 0
Dn Type= 2
Boundary for River Rch & Prof#=128,54,2
Up Type= 0
Dn Type= 2

--- 128_ras.g01 (geometry) ---

Geom Title=128
Program Version=4.10

River Reach=128,54
Reach XY= 30
1203603.78333394621342.5055790441203365.31598129621629.660032527
1202787.03262595621452.7967568471202161.05578933620964.932299873
1202133.23459484620881.4687244911202247.50020199620768.196724917
1202201.79395381620628.0971519831201278.72652127619836.186818896
1201070.06757922619793.461422846 1200771.9833802619866.988867572
 1200477.8736272619596.7258674611200195.68724934619570.891911569
1199517.04887584 619264.858818471199340.18558346 619275.78857759
1199085.82038991 618978.697998311199235.85609368618603.111901175
1198947.70803295618618.0161194771198748.98522821618479.903778973
1198548.27520285618601.1246929711198557.21768876617209.071475755
1198439.77930309616805.9425999681198705.61254567616379.276052316
1198623.94589426616072.609479013 1198325.6126355 615605.10962644
1197574.77951827615418.4430368341197189.33095951615136.181850106
1196888.49772493615482.0150894291196446.83119704615774.515015297
1195733.49808158616029.5149601391195426.53493278  615733.7917045

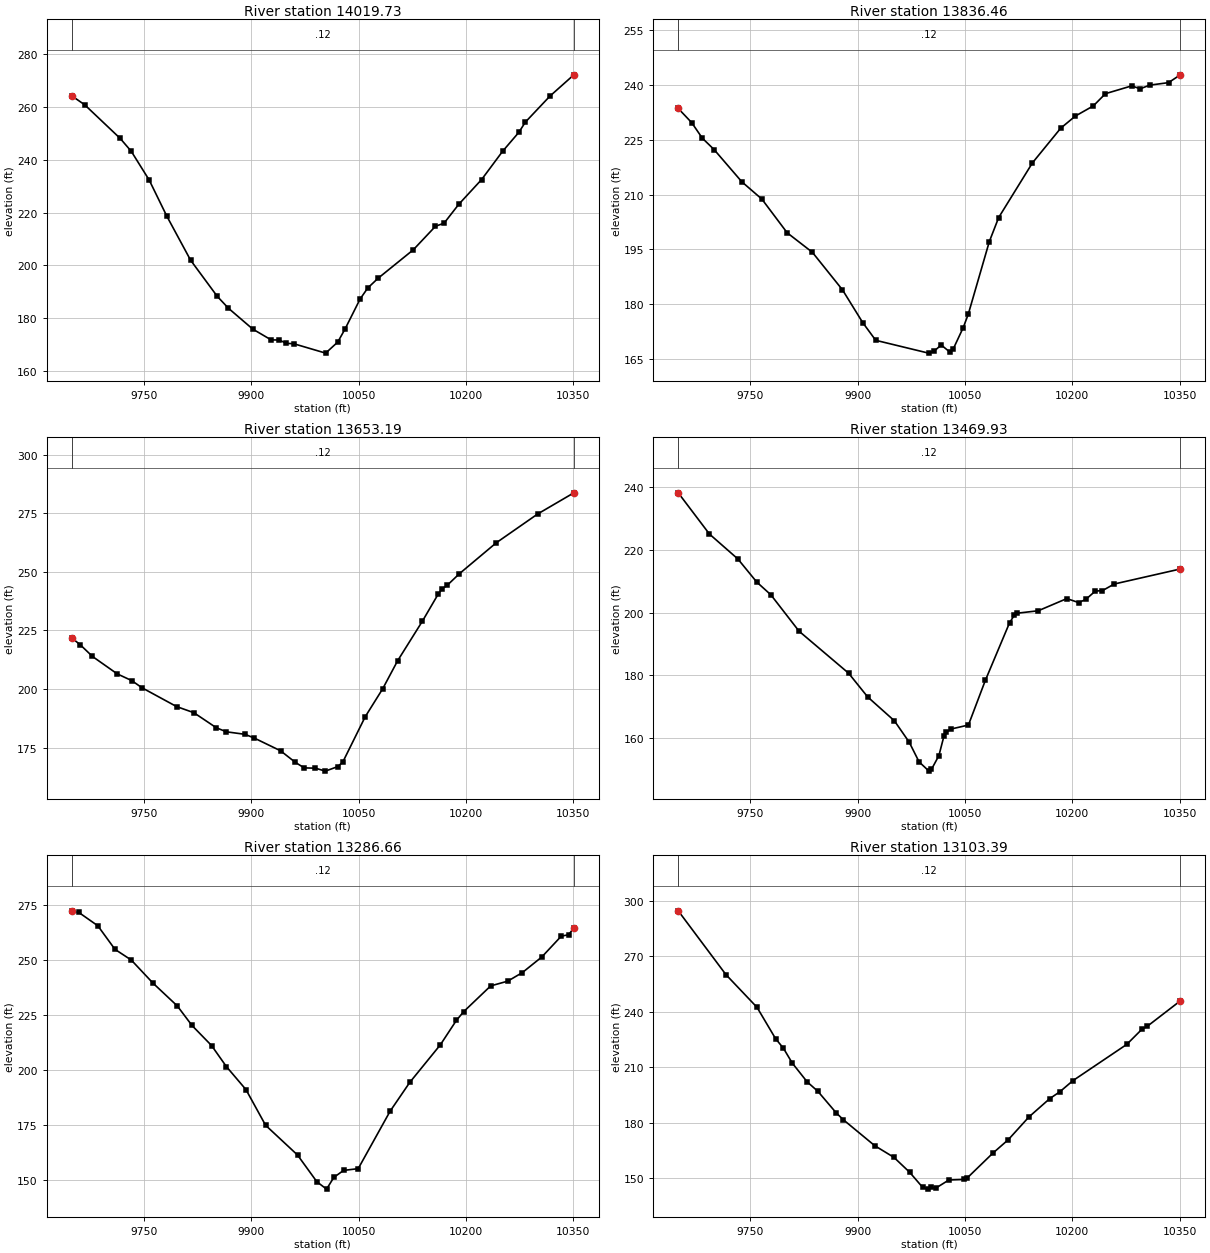
Type RM Length L Ch R = 1 ,14019.73,183.267100,183.267100,183.267100
XS GIS Cut Line= 6
1203332.65682783621135.7352013661203393.10039544621217.821580689
1203463.51842471621279.7824142171203534.55655262621320.687746721
1203719.84374761621392.0190569611203885.66377409621541.812228812
#Sta/Elev= 30
9649.144 264.1519667.323260.73569716.844248.03539732.314  243.169757.362232.2904
9782.209218.51529815.201  201.989852.457188.30559868.094183.79529902.176175.8858
9927.984171.79579938.977171.78859949.036 170.5139959.562170.350810003.99166.8086
10020.93171.003310031.29 176.02210052.11187.261810062.87191.457910077.21 195.116
10126.58205.922210157.52214.809510169.52215.969410190.09223.122110221.96232.4763
10251.31243.162110273.95 250.31910283.17254.219110317.51264.0538 10350.9272.0986
#Mann= 3 , 0 , 0
9649.144    0.12       09649.144    0.12       0 10350.9    0.12       0
#XS Ineff= 2 , 0
       0                               0
Bank Sta=9649.144,10350.9
Exp/Cntr=0.3,0.1

Type RM Length L Ch R = 1 ,13836.46,183.267100,183.267100,183.267100
XS GIS Cut Line= 6
1203291.62358122621226.0185577021203328.38580959621294.022240321
 1203367.9649135621349.0254579681203618.80291585621602.930971672
 1203682.9929361621680.2083364431203739.39619405621761.855565537
#Sta/Elev= 30
9649.081233.60729667.955229.7042 9682.69225.46889699.161222.33999737.964213.4967
9766.049208.73469801.374199.50689836.617194.1527 9878.67 183.8619907.142174.8295
9925.178170.0148    9999166.500310006.44166.990510016.74168.734410029.23166.7209
10033.79167.751510047.47 173.49510054.54177.169610083.94197.076310097.06203.6982
10144.31218.702810183.82228.203110204.25231.5206 10229.4 234.316 10246.3237.6582
10282.87239.792510295.02239.011110307.99239.993710334.46240.686610350.97242.8303
#Mann= 3 , 0 , 0
9649.081    0.12       09649.081    0.12       010350.97    0.12       0
#XS Ineff= 2 , 0
       0                               0
Bank Sta=9649.081,10350.97
Exp/Cntr=0.3,0.1

Type RM Length L Ch R = 1 ,13653.19,183.267100,183.267100,183.267100
XS GIS Cut Line= 6
1203265.93552153621294.1111417311203323.03027888621465.549358425
1203382.11352806621608.8854526521203431.08342093621747.079725374
1203465.90981445621857.4789753761203493.26910755621957.595338532
#Sta/Elev= 30
9649.032221.76449660.682218.94729677.972213.89059712.552206.45579733.023203.5547
9747.132200.53319795.544192.4921 9819.75189.86959851.203183.42249865.252181.7108
 9891.18 180.6429904.069179.05719940.925173.61199961.289168.73719973.901166.3033
9989.731166.180310003.56164.920110020.98166.862910027.95168.803710059.31188.1571
 10083.7200.076810104.61212.061910139.35229.015910161.43240.577410166.87 242.787
10173.75244.228610190.95249.224310242.55262.442510300.42274.742410350.97283.7696
#Mann= 3 , 0 , 0
9649.032    0.12       09649.032    0.12       010350.97    0.12       0
#XS Ineff= 2 , 0
       0                               0
Bank Sta=9649.032,10350.97
Exp/Cntr=0.3,0.1

Type RM Length L Ch R = 1 ,13469.93,183.267100,183.267100,183.267100
XS GIS Cut Line= 6
1203225.68776366621258.7292805241203241.70495525621382.334333491
1203240.47803749621480.3164567751203227.44455098621546.842297202
1203175.07661194621723.9023296291203143.44872871621948.071714213
#Sta/Elev= 30
9649.081238.21059692.699225.06619732.459217.11459758.839 209.7579778.602205.6818
9817.988194.08389887.165180.71189913.874 173.1339951.217165.52279971.946158.7054
9985.765152.41829999.594149.467810003.08 150.03410013.46 154.41410020.38160.5244
10023.84161.953610030.76162.909610054.75164.165610078.41178.4184 10112.2196.7521
10118.96199.211910122.34199.808210152.33200.601910192.27204.486110208.92203.2081
 10218.9204.238710232.14206.883110242.05207.020410258.57209.133610350.94 213.925
#Mann= 3 , 0 , 0
9649.081    0.12       09649.081    0.12       010350.94    0.12       0
#XS Ineff= 2 , 0
       0                               0
Bank Sta=9649.081,10350.94
Exp/Cntr=0.3,0.1

Type RM Length L Ch R = 1 ,13286.66,183.267100,183.267100,183.267100
XS GIS Cut Line= 6
1203123.03140916621210.2828141481203108.94042758621286.332858257
1203092.62661276621352.1360550511203042.54186413621515.989044946
1203026.34453934621579.8894764931202935.94718179621886.353688816
#Sta/Elev= 30
 9649.04272.52399658.783271.81089685.477265.72149709.434 255.0059732.266250.1317
9762.687239.60169796.523 229.2759817.107220.38149844.553211.20889865.137201.6933
9892.582191.18879920.028 174.9699964.627161.44999991.731149.266610005.26145.9197
10015.41 151.24810028.95 154.426 10049.5155.235410094.12181.373910121.57194.4679
10164.37211.583410186.77222.688210197.07226.689810234.68 238.36610258.52240.5283
10278.96244.417910306.21251.537810333.45261.016110343.67261.637910350.98264.7659
#Mann= 3 , 0 , 0
 9649.04    0.12       0 9649.04    0.12       010350.98    0.12       0
#XS Ineff= 2 , 0
       0                               0
Bank Sta=9649.04,10350.98
Exp/Cntr=0.3,0.1

Type RM Length L Ch R = 1 ,13103.39,183.267100,183.267100,183.267100
XS GIS Cut Line= 6
 1203016.8988018621172.4236534541202974.24010078621265.211054124
1202904.43025566621400.5634828211202849.38862861621513.044494382
1202770.76858674621683.3533158811202716.92994857621806.875474082
#Sta/Elev= 30
9649.024294.5379 9715.68260.05319759.187242.33829785.027225.45589796.102220.2242
9808.421212.22479829.325202.02699844.207196.95189869.932185.26389879.994181.5195
9923.757167.53429950.652161.20499972.572153.16369990.838144.95169998.145144.0423
10001.81145.0224 10009.1144.573710027.35148.978110049.04 149.26910052.66149.9322
10088.79163.457810110.47170.771710139.38183.091610168.29192.940210182.74196.7472
10200.81202.695310276.12222.310510297.59230.604810304.75232.080710350.99245.8496
#Mann= 3 , 0 , 0
9649.024    0.12       09649.024    0.12       010350.99    0.12       0
#XS Ineff= 2 , 0
       0                               0
Bank Sta=9649.024,10350.99
Exp/Cntr=0.3,0.1

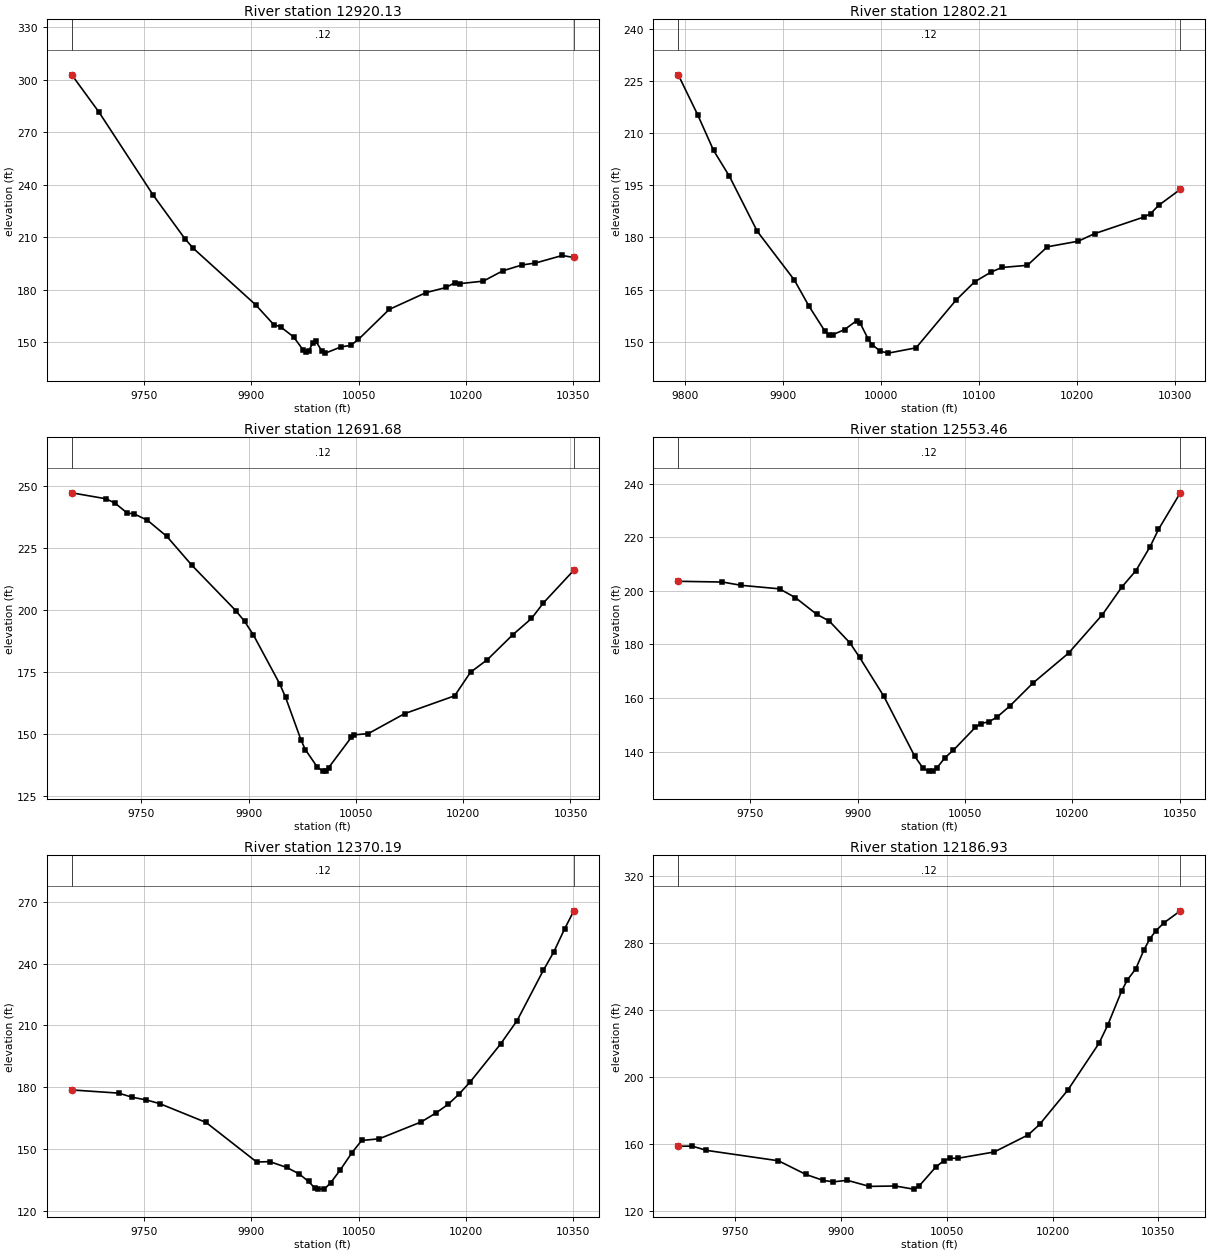
Type RM Length L Ch R = 1 ,12920.13,117.914500,117.914500,117.914500
XS GIS Cut Line= 6
 1202935.2337651621113.0094500781202879.64767694621198.671762045
1202813.56167712621283.9803301481202677.82063908621417.451421091
1202628.03439728621474.2385813561202503.06565849621661.965649604
#Sta/Elev= 30
9649.082302.82629687.141281.49839763.151 233.9579807.133209.26269818.721203.8188
9906.095171.48089931.402160.15299941.017158.87479959.162153.13389972.551145.6165
9977.014 144.5349980.475145.2384 9985.94149.63399990.154150.7384    9999144.8444
10003.56  143.8710025.85147.489610038.91148.261410049.69151.674310092.75168.8137
10144.16178.418410172.33181.361810184.47184.115210192.43   183.610224.28184.9834
10251.52190.874210278.53194.229710297.21195.333110334.61199.636710350.89198.4962
#Mann= 3 , 0 , 0
9649.082    0.12       09649.082    0.12       010350.89    0.12       0
#XS Ineff= 2 , 0
       0                               0
Bank Sta=9649.082,10350.89
Exp/Cntr=0.3,0.1

Type RM Length L Ch R = 1 ,12802.21,110.532600,110.532600,110.532600
XS GIS Cut Line= 3
1202751.85167816621134.8689108341202620.60993865621315.726429939
1202450.15572819621549.400746644
#Sta/Elev= 30
9793.065226.86229812.953215.33099829.168205.07489845.382197.60349873.758181.7814
 9911.59167.76559926.455160.26939942.669153.08129946.723151.97869950.777151.9844
9962.938153.46819975.099156.00589978.624155.44399987.259 150.6139991.313149.0648
 9999.42147.230110007.53146.685510035.94148.216310076.55161.898610095.66167.2154
10112.36170.0127 10123.5171.355610149.64171.986210169.95 177.31410201.44178.9231
10218.14181.094710268.24185.862810275.53186.899210283.66189.262210305.76193.8621
#Mann= 3 , 0 , 0
9793.065    0.12       09793.065    0.12       010305.76    0.12       0
#XS Ineff= 2 , 0
       0                               0
Bank Sta=9793.065,10305.76
Exp/Cntr=0.3,0.1

Type RM Length L Ch R = 1 ,12691.68,138.216600,138.216600,138.216600
XS GIS Cut Line= 6
1202759.10018442620959.4688929571202644.61966517621099.288602053
1202581.62822897621182.0575087981202542.85719957621237.027143561
1202434.72310919621395.299667636 1202347.9314673 621527.69617547
#Sta/Elev= 30
9652.709247.14089700.914244.72169713.634242.88179730.595238.90499739.076238.7525
9758.498236.08579785.719229.53569820.644217.92869881.866199.68339894.234195.3582
9906.733189.79079943.544170.04669951.572164.72199973.491147.26739979.185 143.625
9996.266136.429210003.76134.910410007.75135.081810011.72 136.26410043.51 148.519
10047.48149.521510067.35150.0467 10118.2158.106310187.99165.277310210.22174.7864
10233.75179.858410269.06189.841510295.46 196.46710312.21202.766910354.69215.9388
#Mann= 3 , 0 , 0
9652.709    0.12       09652.709    0.12       010354.69    0.12       0
#XS Ineff= 2 , 0
       0                               0
Bank Sta=9652.709,10354.69
Exp/Cntr=0.3,0.1

Type RM Length L Ch R = 1 ,12553.46,183.267100,183.267100,183.267100
XS GIS Cut Line= 6
1202652.30485772620899.5758687361202560.89809977620984.325638992
1202489.48916306 621067.474448921202442.04820002621138.192471586
1202327.76334152621326.3079242311202238.51305217621461.893602876
#Sta/Elev= 30
9649.048  203.579710.917 203.2919737.199202.06169790.645200.75779812.963197.4509
9842.575191.27149860.111188.75989889.116180.58179902.532175.20999936.524160.6543
9979.723 138.2619991.279133.85269998.992  132.7410004.76132.7927 10010.5133.8605
10022.01137.784410033.52140.493610064.21149.018510071.88150.474610083.39151.1527
10094.89152.9394 10112.4156.966110144.76165.549210194.77176.7716 10242.1191.1337
 10269.4201.482310289.04207.586510308.68 216.46110320.46222.925510350.99236.5787
#Mann= 3 , 0 , 0
9649.048    0.12       09649.048    0.12       010350.99    0.12       0
#XS Ineff= 2 , 0
       0                               0
Bank Sta=9649.048,10350.99
Exp/Cntr=0.3,0.1

Type RM Length L Ch R = 1 ,12370.19,183.267100,183.267100,183.267100
XS GIS Cut Line= 6
1202551.87664976620861.3230792591202395.99700647620952.712520049
1202361.55505068620976.9022306031202330.98770043621003.166343629
1202255.16195159621085.2038544461202047.34061943621337.810498561
#Sta/Elev= 30
 9649.05178.66279714.712177.10949733.728175.09099752.743173.84079771.759172.0414
9836.773162.85749907.541143.61699925.884143.80149949.462140.98489966.749137.8889
9980.049134.15299988.916130.94769993.349130.4996 10002.2130.431410010.95133.5119
10024.06 139.59210040.91148.206710054.34154.080410078.83154.903810137.81163.1442
10158.88167.616110175.73171.807610189.98176.478310205.68 182.39510248.48200.9581
10271.72212.4269 10308.4236.877910322.81245.666210338.13257.019310350.99265.7577
#Mann= 3 , 0 , 0
 9649.05    0.12       0 9649.05    0.12       010350.99    0.12       0
#XS Ineff= 2 , 0
       0                               0
Bank Sta=9649.05,10350.99
Exp/Cntr=0.3,0.1

Type RM Length L Ch R = 1 ,12186.93,269.720700,269.720700,269.720700
XS GIS Cut Line= 4
1202440.74001688620796.0544121121202240.37109014620873.748485729
1202075.44156545620981.4297456741201830.09185925621154.537593916
#Sta/Elev= 30
9668.968158.89719688.724158.9757 9709.05 156.4349811.097150.23069849.804142.1234
9874.436 138.5279889.038137.64789908.629138.59519939.974134.95149976.867135.1789
10002.67133.3148 10010.5135.088810034.01146.370210045.77150.335710054.88151.7521
10065.36151.702910117.17155.478110165.35165.674110181.43171.866110221.57192.4057
10265.73220.294410278.17231.170510297.86251.482510305.89258.017610318.01 264.792
10329.39275.875410338.01282.702410346.04287.224410357.84292.141710381.11299.3237
#Mann= 3 , 0 , 0
9668.968    0.12       09668.968    0.12       010381.11    0.12       0
#XS Ineff= 2 , 0
       0                               0
Bank Sta=9668.968,10381.11
Exp/Cntr=0.3,0.1

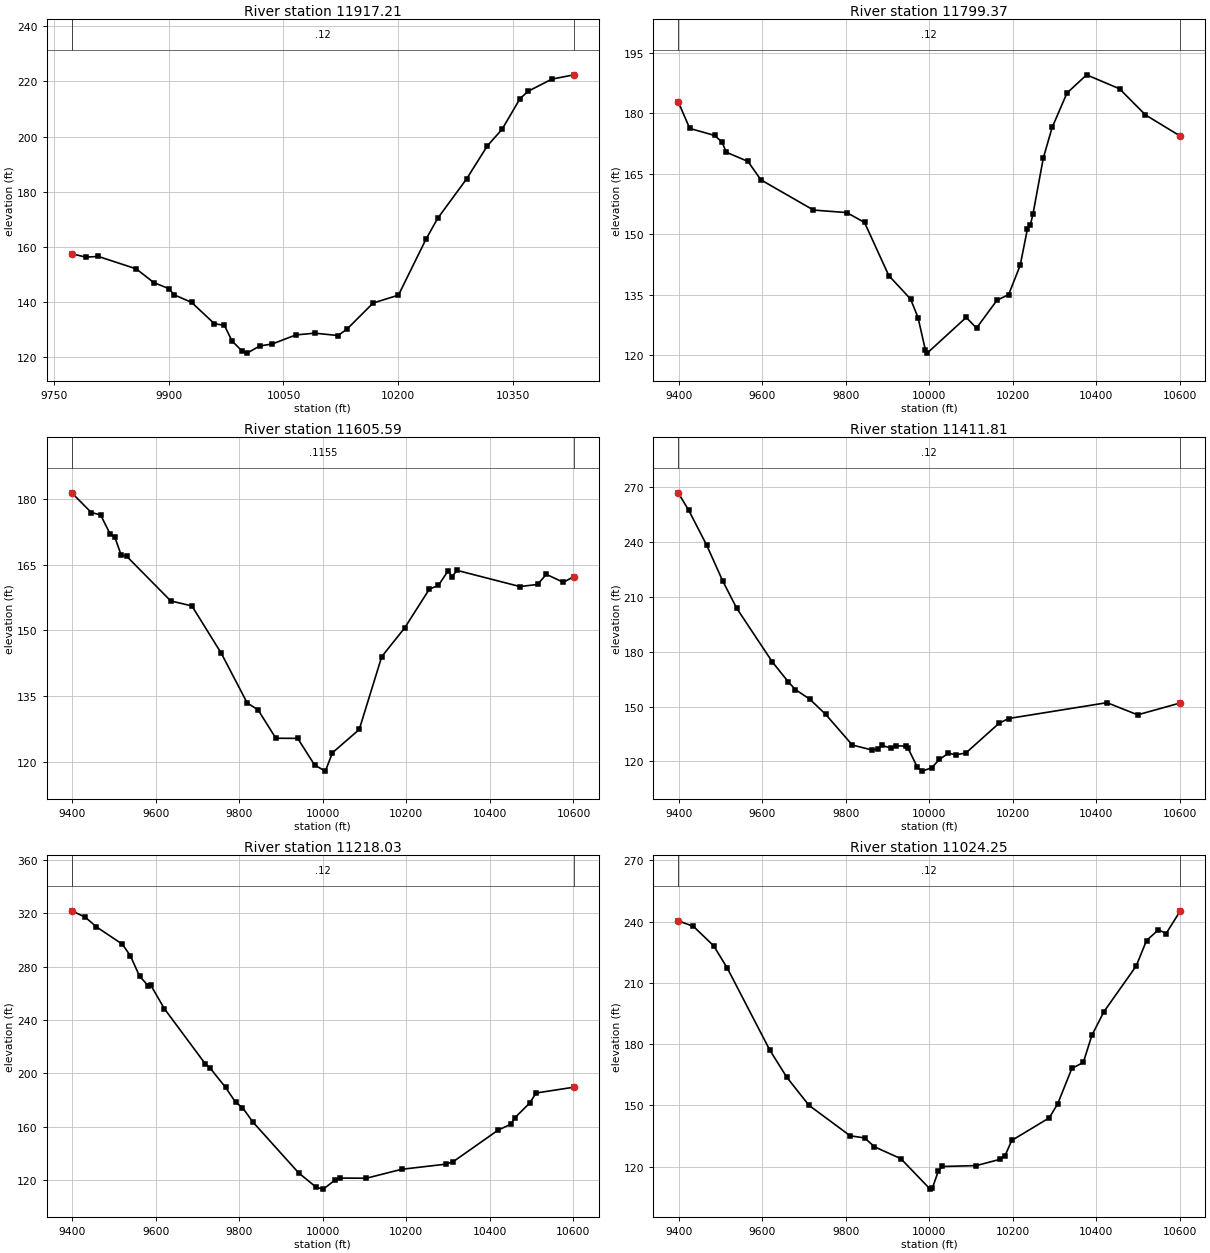
Type RM Length L Ch R = 1 ,11917.21,117.837100,117.837100,117.837100
XS GIS Cut Line= 4
1202470.72720319620704.729799241 1202195.3903107620731.990877703
1202154.49869299620748.3475247921201866.89431515620921.455373034
#Sta/Elev= 30
9773.231157.57039791.466156.34919807.951156.59019857.404152.10799880.482147.1246
9900.263144.92939906.857142.71949929.935139.94959959.607132.23919972.794131.6329
9982.685125.98529995.872122.334310002.47121.572310018.95124.165110035.43124.8909
 10066.2128.164810090.93128.800410121.31127.9503 10132.8130.195910167.26139.7267
10200.32142.572110236.19162.763710251.51170.354510289.39184.659110316.61196.6836
10335.75202.627710359.37 213.79110370.22216.477710400.85220.814310429.64222.3774
#Mann= 3 , 0 , 0
9773.231    0.12       09773.231    0.12       010429.64    0.12       0
#XS Ineff= 2 , 0
       0                               0
Bank Sta=9773.231,10429.64
Exp/Cntr=0.3,0.1

Type RM Length L Ch R = 1 ,11799.37,193.778900,193.778900,193.778900
XS GIS Cut Line= 6
1202649.43256744620231.0872214521202508.25332404620363.447785446
1202254.98812288620565.1772399231202145.84395842620667.135710735
1201858.85664236620783.0550056051201669.19603121620902.440905408
#Sta/Elev= 30
 9399.08 182.8389426.603 176.2639486.234174.5075 9504.14172.84329513.849170.3724
9566.172168.05829596.771163.51759722.743156.01549802.459155.38679844.974152.9449
9903.004 139.7819955.247133.94279972.988129.37179990.571121.34659994.933120.5457
10088.33129.401110113.01126.763910162.09133.6669 10189.8135.044610217.51142.2914
10234.83151.321410241.76152.311510248.22155.047410272.93168.935810294.02176.4894
10329.51185.020810376.54189.545110455.27186.087510517.42179.609810600.82174.3445
#Mann= 3 , 0 , 0
 9399.08    0.12       0 9399.08    0.12       010600.82    0.12       0
#XS Ineff= 2 , 0
       09932.055                       0
Bank Sta=9399.08,10600.82
Exp/Cntr=0.3,0.1

Type RM Length L Ch R = 1 ,11605.59,193.778800,193.778800,193.778800
XS GIS Cut Line= 6
1202463.17671375620066.7070229421202071.38245663620471.123408608
1201980.97112956620570.2820603831201896.82606963620639.943031416
1201687.66678711620791.8520902391201582.07527781620878.538967754
#Sta/Elev= 30
9399.037181.36839445.808176.87079468.117176.32629490.426172.04629501.809 171.345
9517.196167.17359530.713166.85829636.043156.67759686.609155.54749756.971 144.731
9818.859133.41369845.185131.78819887.564125.33169939.842125.30539980.381119.2177
10006.08117.825810023.08122.020610087.18127.331210141.04143.961510195.81150.5082
10255.07159.3778 10276.9160.253110300.07163.582210309.21162.216710321.33163.6616
10471.97159.964310513.99160.448510535.11162.758510575.87 160.92910600.94162.2595
#Mann= 3 , 0 , 0
9399.037  0.1155       09399.037  0.1155       010600.94  0.1155       0
#XS Ineff= 2 , 0
       09922.664                       0
Bank Sta=9399.037,10600.94
Exp/Cntr=0.3,0.1

Type RM Length L Ch R = 1 ,11411.81,193.778900,193.778900,193.778900
XS GIS Cut Line= 6
1202284.25211949619907.7050932131201973.71735087620283.941126388
1201883.46448457620425.4370267551201838.12850527 620482.91562628
1201754.83769398 620570.190447451201500.05865166620813.257682237
#Sta/Elev= 30
 9399.05266.86439424.346257.22719466.886 238.3639505.704218.58329539.205203.6717
9624.247174.40779662.571163.45199679.587 159.2439713.619154.09349751.905145.7298
9815.716128.9579 9862.51126.23039876.796126.76549887.123128.68749908.208127.2901
9920.761128.51899944.621128.34049948.667127.45079971.742116.69259983.092114.6664
10005.71 116.51510024.45121.091410045.96124.478210063.66123.566210087.86124.6218
10166.61140.750510189.69143.435610425.49152.1024 10498.8145.454110600.97151.9573
#Mann= 3 , 0 , 0
 9399.05    0.12       0 9399.05    0.12       010600.97    0.12       0
#XS Ineff= 2 , 0
       0 9920.64                       0
Bank Sta=9399.05,10600.97
Exp/Cntr=0.3,0.1

Type RM Length L Ch R = 1 ,11218.03,193.778900,193.778900,193.778900
XS GIS Cut Line= 6
1202130.74644668619775.1790725411201918.36858717620054.267677383
1201775.24901344620255.9757436631201713.36813607620336.192371344
1201599.63457952620476.3163070791201389.68193622620720.464622914
#Sta/Elev= 30
9399.015321.94149431.005317.23879458.094309.89879519.978296.9382 9539.36288.2117
9561.206272.98089581.819265.7796 9588.12266.19089620.626248.54929718.145207.3621
9730.238203.98759767.079189.50629791.446178.24689807.691174.34929832.058163.7295
9941.828 125.479 9984.37 114.519   10001113.185310029.79120.080110042.16121.5057
10104.17121.353410188.68128.058110294.16131.896910311.99133.741310419.96157.4992
10450.15161.887310459.11166.478310495.44177.819310510.53185.279610600.97189.6365
#Mann= 3 , 0 , 0
9399.015    0.12       09399.015    0.12       010600.97    0.12       0
#XS Ineff= 2 , 0
       0                               0
Bank Sta=9399.015,10600.97
Exp/Cntr=0.3,0.1

Type RM Length L Ch R = 1 ,11024.25,193.778900,193.778900,193.778900
XS GIS Cut Line= 6
1201960.98543624619668.2801786951201714.36660542620004.814143175
1201670.65454595620069.1240404081201577.21078137620213.847823554
1201526.84751959620286.7734936911201261.09467968620645.066686408
#Sta/Elev= 30
9399.013240.39799435.308 237.7169484.118228.11379516.658217.17059618.344177.0679
9659.019 163.7939711.896150.10249810.641 135.1719845.384134.11489868.715129.7914
9931.954123.953210002.09109.056710007.49109.5606 10021.7117.952310031.45120.1357
10112.65120.584710168.81123.611610181.06125.2975 10197.4132.878110287.27143.9556
10307.69150.924510341.24168.121610368.77171.079810389.39184.419810418.34195.9928
10495.44218.3109 10520.1230.777810548.69236.015110567.03234.195110600.99245.3057
#Mann= 3 , 0 , 0
9399.013    0.12       09399.013    0.12       010600.99    0.12       0
#XS Ineff= 2 , 0
       0                               0
Bank Sta=9399.013,10600.99
Exp/Cntr=0.3,0.1

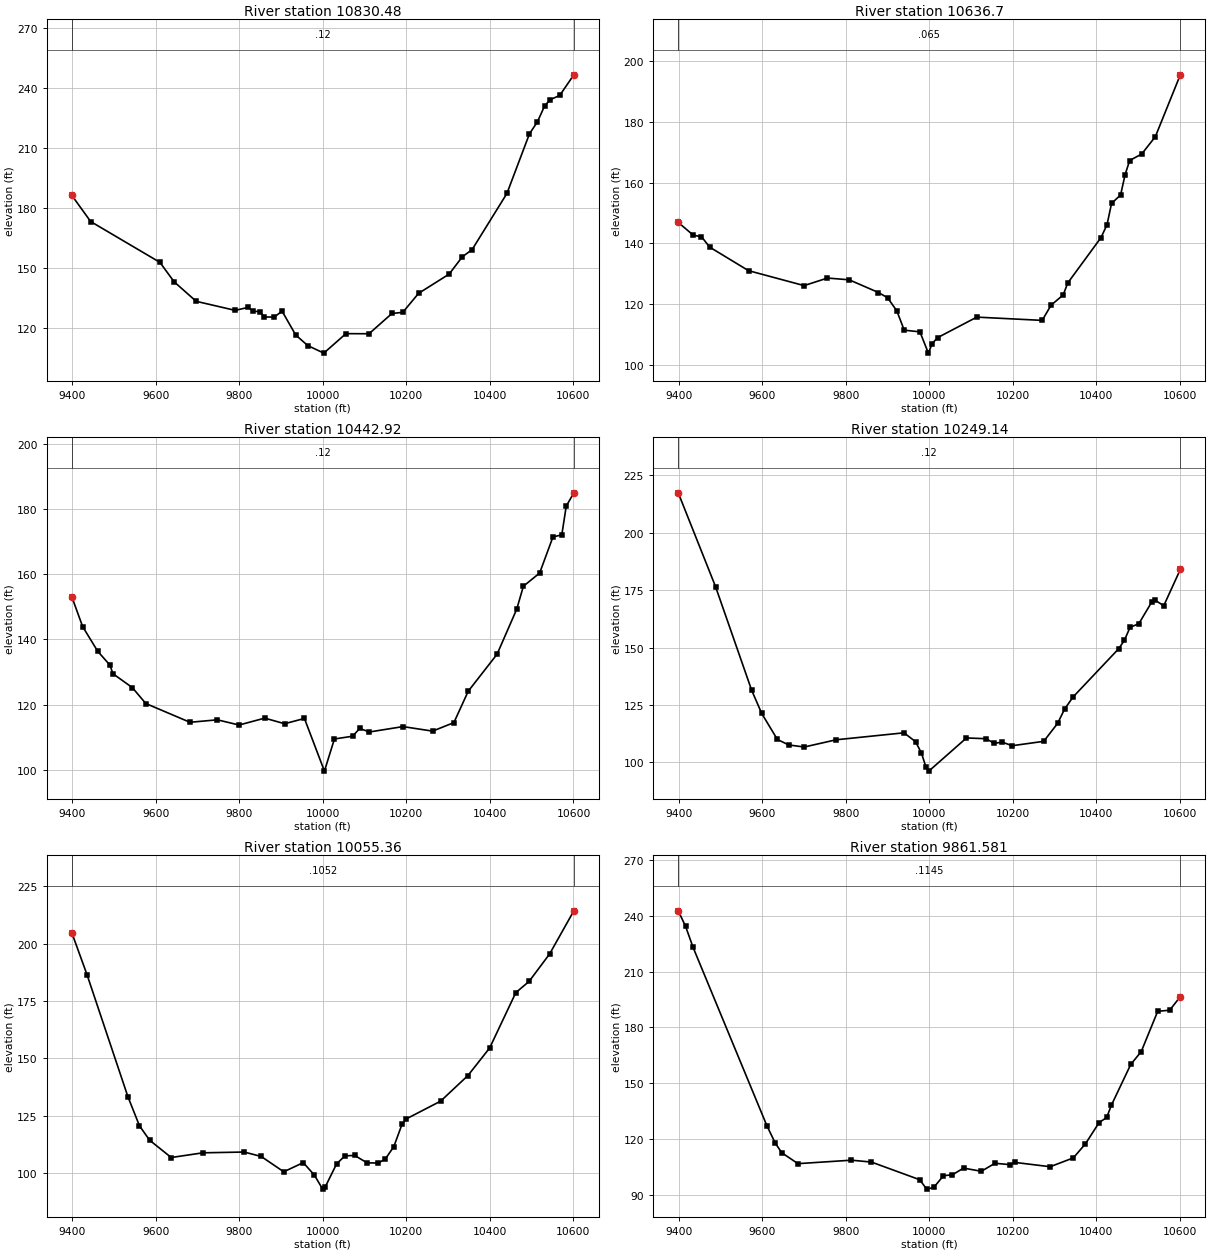
Type RM Length L Ch R = 1 ,10830.48,193.778900,193.778900,193.778900
XS GIS Cut Line= 6
1201845.23316312619575.5396668851201613.35421608619884.054888985
1201393.01674694620103.7201925851201321.58525312620186.201386396
1201232.08850795620316.1844254051201111.21943606620520.606768278
#Sta/Elev= 30
9399.037186.35179444.261 173.2399610.056152.81769644.027143.09869696.832133.3345
9790.155 128.8029820.778130.26969833.945128.34049849.265128.19149859.914125.4945
9883.589125.44839902.529128.39339935.121116.47629963.979111.195210002.39107.4142
10055.34117.159410110.66117.107210165.51127.247110191.45 127.81310229.31137.3216
10302.42 146.94410333.81155.557410357.45159.204910440.78187.301210494.74217.1311
 10513.8223.124210531.03231.093610544.29234.161410567.16236.321310600.95246.6164
#Mann= 3 , 0 , 0
9399.037    0.12       09399.037    0.12       010600.95    0.12       0
#XS Ineff= 2 , 0
       0                10178.31       0
Bank Sta=9399.037,10600.95
Exp/Cntr=0.3,0.1

Type RM Length L Ch R = 1 , 10636.7,193.778900,193.778900,193.778900
XS GIS Cut Line= 6
1201683.34686559619404.4705173281201462.73514463619742.310170609
1201286.85106876619947.1720143241201238.79058623 620013.67524962
1201181.36316975 620117.542621451201043.61214159620414.495736555
#Sta/Elev= 30
9399.064146.92639435.302142.69689454.717142.23939474.132138.81729567.324131.0638
9700.404126.15059756.218128.63659808.303128.05829878.429123.87629900.176122.1628
9922.272117.85919940.053111.50389977.651110.94819997.841103.957510007.04107.0861
10019.73 109.036 10113.8115.793410270.29114.719110291.64119.729910320.58 123.077
10331.43127.003410410.99 141.90410425.46146.153910436.31153.159510458.01155.9574
10468.86162.659210479.71167.271610508.64169.414510541.19175.109110600.95195.4352
#Mann= 3 , 0 , 0
9399.064   0.065       09399.064   0.065       010600.95   0.065       0
#XS Ineff= 2 , 0
       0                10170.04       0
Bank Sta=9399.064,10600.95
Exp/Cntr=0.3,0.1

Type RM Length L Ch R = 1 ,10442.92,193.778900,193.778900,193.778900
XS GIS Cut Line= 6
1201372.01561234619244.171891278 1201294.0346058619416.718638205
 1201232.8396103619583.1385792831201159.31765486619844.804100778
1201104.00900485620098.6447272171201000.56959289620383.744230946
#Sta/Elev= 30
9399.027153.09839425.089 143.9249461.328136.32859490.319 132.1519497.567129.4915
9544.086125.22849576.248120.36329682.004114.61179747.671115.3657 9799.57113.7692
9860.987115.89059908.482114.16599955.976115.787510003.8599.6441710027.75109.4994
10071.43110.336910088.16112.715710111.58111.639710191.86113.290110262.77111.9036
10313.76  114.51 10348.1124.129310417.17135.476910464.13149.248110480.15156.3063
10519.06 160.34110550.89171.400810572.11172.045210582.72180.851110600.93184.9224
#Mann= 3 , 0 , 0
9399.027    0.12       09399.027    0.12       010600.93    0.12       0
#XS Ineff= 2 , 0
       09911.432         10155.9       0
Bank Sta=9399.027,10600.93
Exp/Cntr=0.3,0.1

Type RM Length L Ch R = 1 ,10249.14,193.778800,193.778800,193.778800
XS GIS Cut Line= 6
1201056.10748582619246.8942851751200951.43146075619605.539573434
1200953.82654248619725.335014494 1201024.7057134620026.687673172
1200994.11200667620211.1812144751200925.38822615620407.055415129
#Sta/Elev= 30
9399.135 217.4069488.338176.57589574.784131.41779598.974121.25119636.419109.9375
9663.509107.54439700.758106.63979777.181109.79439939.606112.82699967.356108.9222
 9981.37103.97339991.88297.990339998.88996.1310710089.06 110.59410135.67 110.254
10155.47108.265810175.19108.752310198.16107.198410273.95109.113710307.16116.9348
10323.92123.164110344.04128.408210453.09149.409810466.82 153.064 10480.7 158.813
10501.56160.362210533.12170.008210540.16170.639810561.28168.225710600.89184.0116
#Mann= 3 , 0 , 0
9399.135    0.12       09399.135    0.12       010600.89    0.12       0
#XS Ineff= 2 , 0
       09863.546        10100.71       0
Bank Sta=9399.135,10600.89
Exp/Cntr=0.3,0.1

Type RM Length L Ch R = 1 ,10055.36,193.778900,193.778900,193.778900
XS GIS Cut Line= 6
1200966.12694058619296.0374178381200896.20791977619489.668889576
1200831.52520293619704.9477095711200778.61622776 619989.66435555
1200739.02930602620145.5882708971200630.14774986620446.905430876
#Sta/Elev= 30
9399.035 204.7639435.447186.48019533.315133.26859561.076120.52519585.368114.2404
9637.143 106.6919712.829108.73859811.804109.0813 9852.57107.14549906.514100.4657
9953.239104.46489979.76199.028669999.65692.9045210006.2994.0409410032.81103.8462
10052.71 107.40910076.06107.603310106.08104.369610132.89104.276910149.72106.0699
10169.92111.4185 10189.6121.1781 10200.3123.582410281.96131.266810347.38142.4366
 10399.3154.434910462.03178.6064 10493.8183.490410542.81195.436710600.96  214.28
#Mann= 3 , 0 , 0
9399.035  0.1052       09399.035  0.1052       010600.96  0.1052       0
#XS Ineff= 2 , 0
       0 9777.58        10073.52       0
Bank Sta=9399.035,10600.96
Exp/Cntr=0.3,0.1

Type RM Length L Ch R = 1 ,9861.581,193.778900,193.778900,193.778900
XS GIS Cut Line= 6
1200941.72529678619238.2451896441200779.84890238619618.752540366
1200720.70639703619698.2638912821200595.56554324619798.370457275
1200523.97544878619881.6511963881200337.85437092620255.598166666
#Sta/Elev= 30
9399.131242.67269416.815 234.2549434.505223.08359611.402127.03639631.358117.7292
9646.781112.55999685.698106.66759813.793108.53319861.698107.51399977.06898.03022
9993.82492.9646510010.6993.8442510034.01100.186710055.41100.677910081.98104.2787
10124.59102.564310157.28106.870910193.77106.122810205.37107.3245 10289.3105.0166
10344.85109.7656 10373.9117.360810406.57128.778910424.72131.502710435.61137.9595
10482.26160.032310507.35166.956210546.79188.635310575.47189.201210600.89196.5117
#Mann= 3 , 0 , 0
9399.131  0.1145       09399.131  0.1145       010600.89  0.1145       0
#XS Ineff= 2 , 0
       09819.642        10113.02       0
Bank Sta=9399.131,10600.89
Exp/Cntr=0.3,0.1

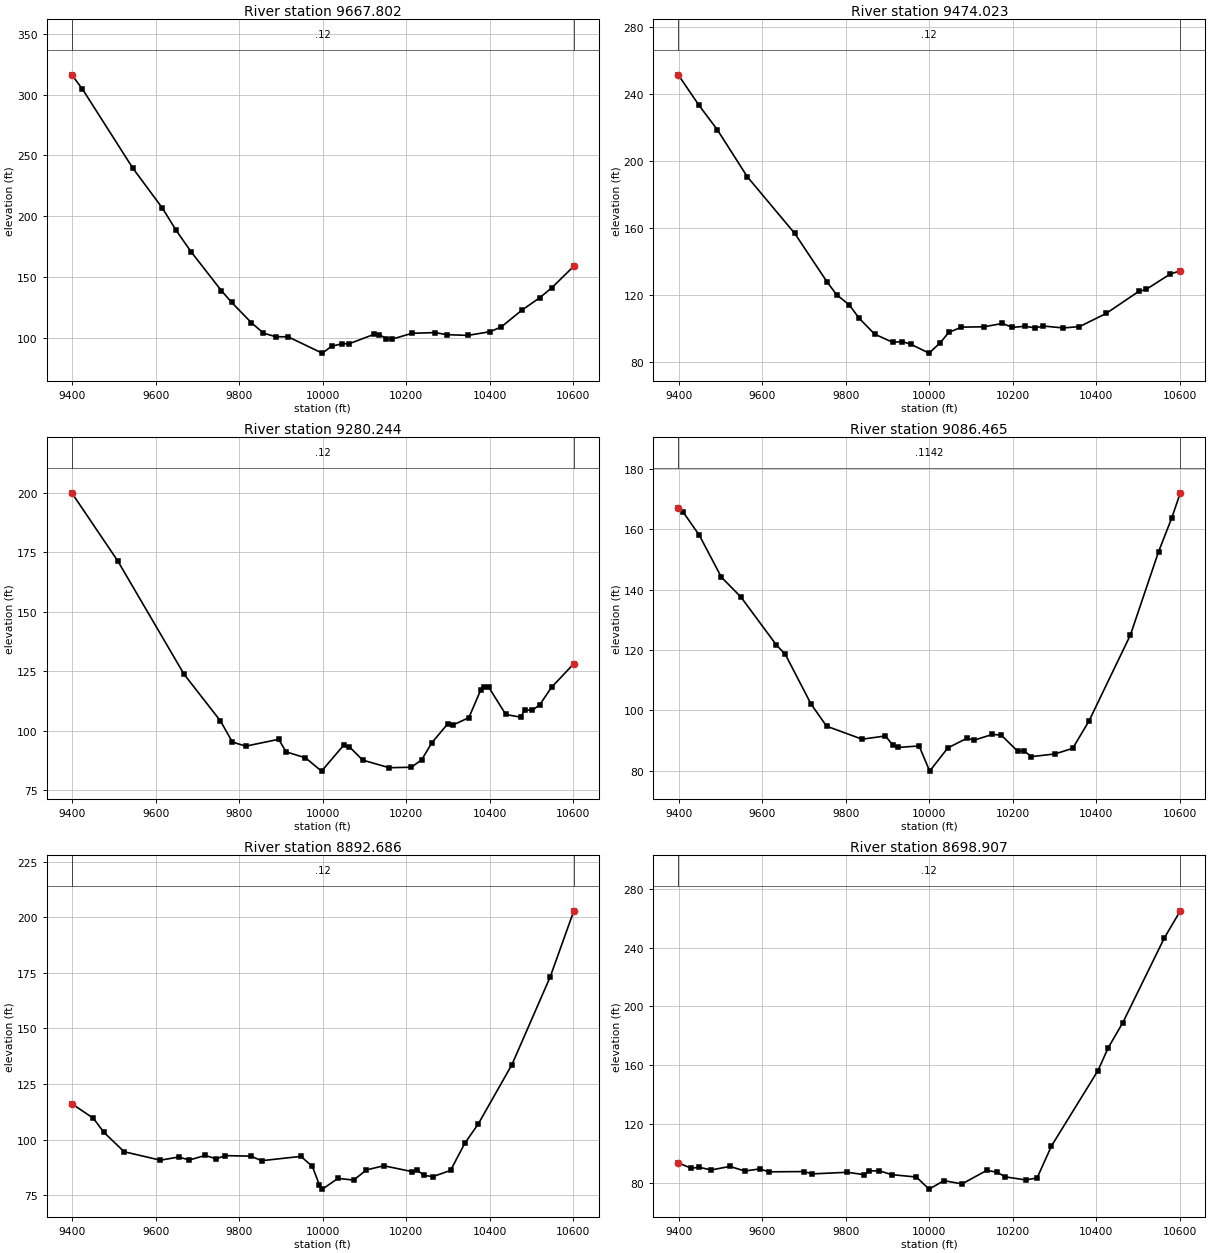
Type RM Length L Ch R = 1 ,9667.802,193.778900,193.778900,193.778900
XS GIS Cut Line= 6
1200776.34921325619074.3816113521200717.01774319619199.082557189
 1200580.5554204619497.4520207271200480.86307898619687.602948149
1200355.85581165619959.5760213831200266.97675877620162.674151959
#Sta/Elev= 30
9399.021316.16219424.251304.6368    9545239.64469615.992206.74179648.722188.5718
9684.799170.84649756.952139.08699781.642129.4351 9828.97112.67679857.968104.1447
9887.204101.18469916.566 101.1439998.60387.7124410021.21  93.34410047.1395.50132
10061.7895.2560210123.42103.218410134.25 102.948 10152.399.7161610166.5399.27731
10213.69103.988310268.66104.560810296.74102.872510347.29102.270810401.27105.3568
10427.71109.344910476.47122.954210519.45133.2231 10548.1141.326310600.99159.1023
#Mann= 3 , 0 , 0
9399.021    0.12       09399.021    0.12       010600.99    0.12       0
#XS Ineff= 2 , 0
       0                10137.73       0
Bank Sta=9399.021,10600.99
Exp/Cntr=0.3,0.1

Type RM Length L Ch R = 1 ,9474.023,193.778900,193.778900,193.778900
XS GIS Cut Line= 6
1200521.30849726619036.4523998521200397.18846997619318.250862296
  1200362.228641619437.6449995461200336.84645064619579.845007126
1200286.74215534619784.6561469221200137.10503646620170.461158051
#Sta/Elev= 30
9399.046251.3935 9448.55233.27169492.458  218.659564.561190.4691 9677.86156.6934
9755.986127.46539778.178120.09349808.681113.94949831.656106.1488 9869.2296.52814
9912.54491.65564 9935.8292.062459955.77190.508379999.36985.1888110026.3191.37247
 10046.597.5297410076.79100.711210130.68100.907510174.94102.902210198.94 100.581
10230.01101.221110254.27100.207810271.75101.400910320.69100.230610359.59 101.023
10423.35108.866310501.28122.028810518.99123.202710575.66132.257710600.96134.4024
#Mann= 3 , 0 , 0
9399.046    0.12       09399.046    0.12       010600.96    0.12       0
#XS Ineff= 2 , 0
       09861.318        10098.97       0
Bank Sta=9399.046,10600.96
Exp/Cntr=0.3,0.1

Type RM Length L Ch R = 1 ,9280.244,193.778900,193.778900,193.778900
XS GIS Cut Line= 6
1200393.30865904619006.194871421 1200356.7573471619074.186185476
1200300.49361457619188.4705374461200170.79497491619484.947043498
1200119.21607284619619.6877619061199922.68678727 620111.34844279
#Sta/Elev= 30
9399.017199.98759509.135171.3467 9667.68123.78389754.997104.11549783.58295.24706
9815.47993.526169894.34896.405179912.21491.113369958.41688.631299997.00283.03096
10049.5493.8387210063.5693.27292 10095.387.6796110158.8984.4625310211.8984.66792
10236.6387.7887410261.3695.0301410299.45 102.98210310.82102.344410349.69105.5029
10377.96117.090410385.02  118.4710396.69118.449910438.02106.844210473.35105.7112
10483.95108.745110501.62108.593410519.28110.922410547.55118.245610600.99128.1848
#Mann= 3 , 0 , 0
9399.017    0.12       09399.017    0.12       010600.99    0.12       0
#XS Ineff= 2 , 0
       09863.976        10058.02       0
Bank Sta=9399.017,10600.99
Exp/Cntr=0.3,0.1

Type RM Length L Ch R = 1 ,9086.465,193.778800,193.778800,193.778800
XS GIS Cut Line= 6
1200272.64952526618919.8680976811200211.09925546619019.358611679
1200151.78313673619123.7999588021200004.49967269 619405.97259577
1199885.39213475619656.7690359751199746.68831854619998.546938273
#Sta/Elev= 30
9399.026167.17729410.754165.77869449.333158.12159502.266 144.1929548.899137.6316
9634.236121.6558 9655.38118.58289717.106102.07959754.11594.778599839.23590.45918
9894.74891.526229913.25288.483479924.811 87.71859975.59888.22157   1000179.87184
10044.2987.5485410090.6690.8180210106.7590.1077510150.84 92.041210172.4591.80475
10212.0786.4024410226.4886.6601310244.2884.6689510300.9385.5748810343.4287.42789
10382.3796.5031810481.51125.016410548.78152.573410580.65163.871410600.98172.1516
#Mann= 3 , 0 , 0
9399.026  0.1142       09399.026  0.1142       010600.98  0.1142       0
#XS Ineff= 2 , 0
       09871.991        10181.09       0
Bank Sta=9399.026,10600.98
Exp/Cntr=0.3,0.1

Type RM Length L Ch R = 1 ,8892.686,193.778900,193.778900,193.778900
XS GIS Cut Line= 6
 1200089.3531177618852.381391188 1199952.3377037619045.760571055
1199861.31379542 619216.45128092 1199823.8644343619313.448520733
1199736.30236257619600.783069541 1199606.2457795619943.693850318
#Sta/Elev= 30
9399.065116.11889450.789109.57599475.401103.37259524.30294.539479611.15290.73408
9655.23292.160659680.43690.795799718.39192.865829744.47791.349369766.65892.78541
9828.42992.53899 9853.3290.496769947.662 92.44699974.98487.928659992.061 79.5152
9998.89177.7216810036.3482.5398910073.7981.7927110104.5686.3626110146.0488.21994
10214.1785.5800510225.5586.2310410242.92 83.881110263.5783.3674710305.8186.12354
10339.9498.3518710372.19107.031310452.83133.728610544.49173.192710600.97202.8337
#Mann= 3 , 0 , 0
9399.065    0.12       09399.065    0.12       010600.97    0.12       0
#XS Ineff= 2 , 0
       09876.362        10254.71       0
Bank Sta=9399.065,10600.97
Exp/Cntr=0.3,0.1

Type RM Length L Ch R = 1 ,8698.907,193.778900,193.778900,193.778900
XS GIS Cut Line= 6
1199956.19555918618817.8730583631199802.81130405618998.534227606
1199701.53360401619163.2606326051199590.61971881619386.996184768
1199498.57924962619663.3121120751199414.16096851619877.439173581
#Sta/Elev= 30
9399.05293.437559430.48789.76457 9448.64 90.47939478.09888.631929522.90591.04622
9558.17787.904529594.772 89.35179615.59287.355619699.87187.533149719.89785.95038
9803.123 87.04139843.90985.472689854.88587.963149880.72388.020299910.174 85.4224
9969.07783.819999999.54875.5811910035.1981.3513110078.2779.1277510137.5488.31477
10161.6387.1275510182.2883.9198210230.4681.85856   1025883.1330610292.58104.9672
10403.83156.260910428.35171.755210463.38188.918510562.57246.429510600.96264.9768
#Mann= 3 , 0 , 0
9399.052    0.12       09399.052    0.12       010600.96    0.12       0
#XS Ineff= 2 , 0
       09907.014                       0
Bank Sta=9399.052,10600.96
Exp/Cntr=0.3,0.1