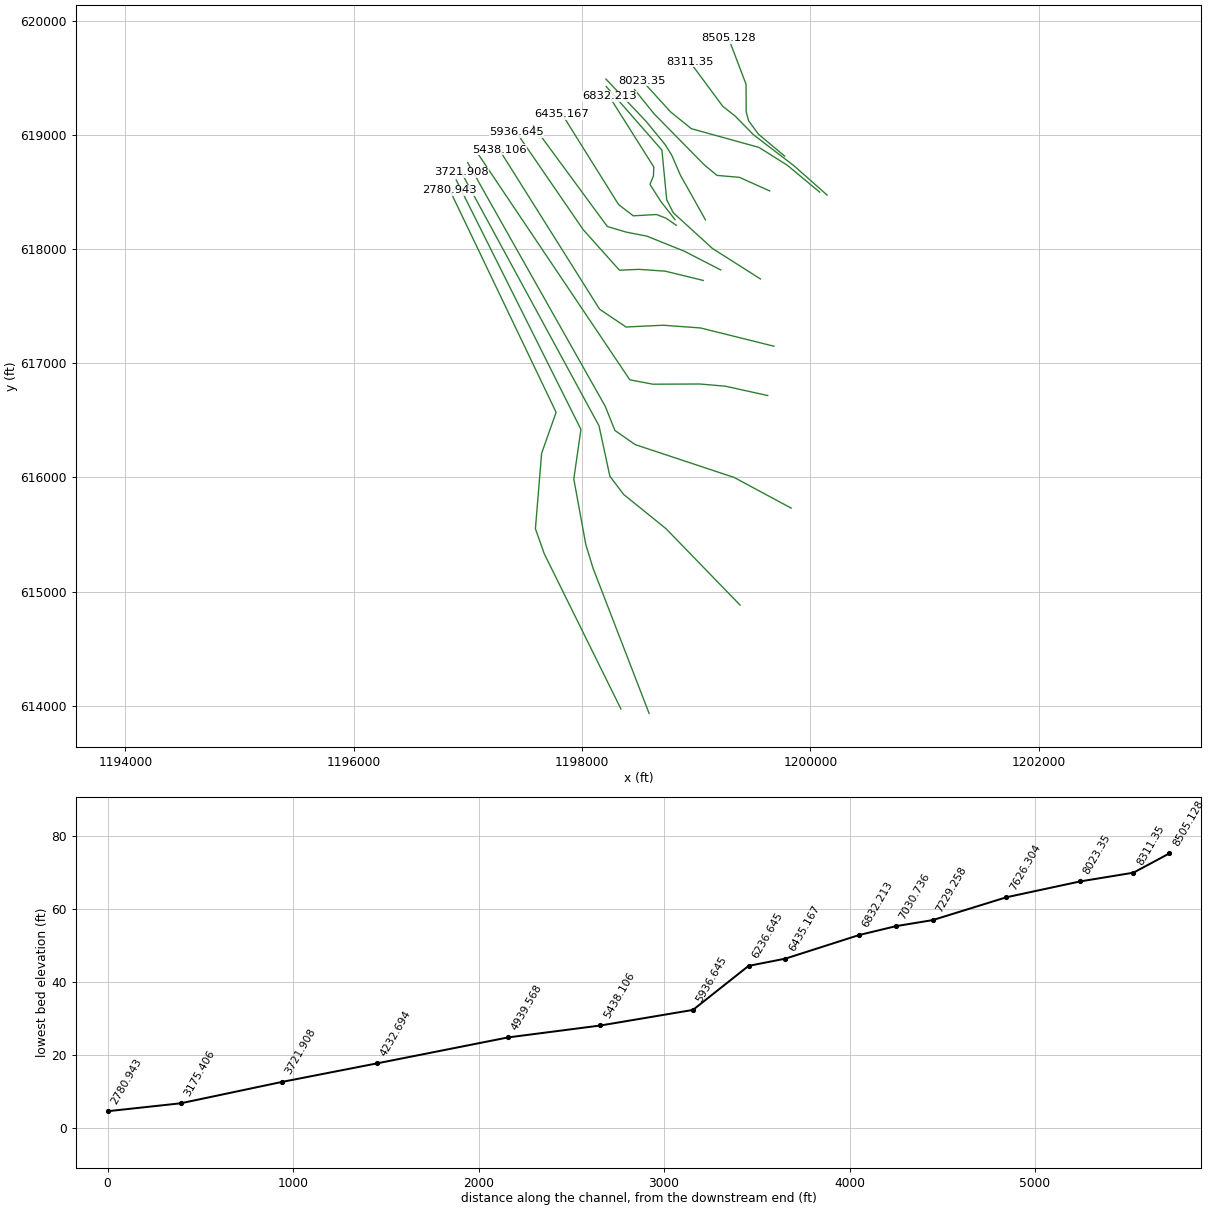
HEC-RAS study 128_ras.prj: 128

--- 128_ras.g01 (geometry) --- (continued)

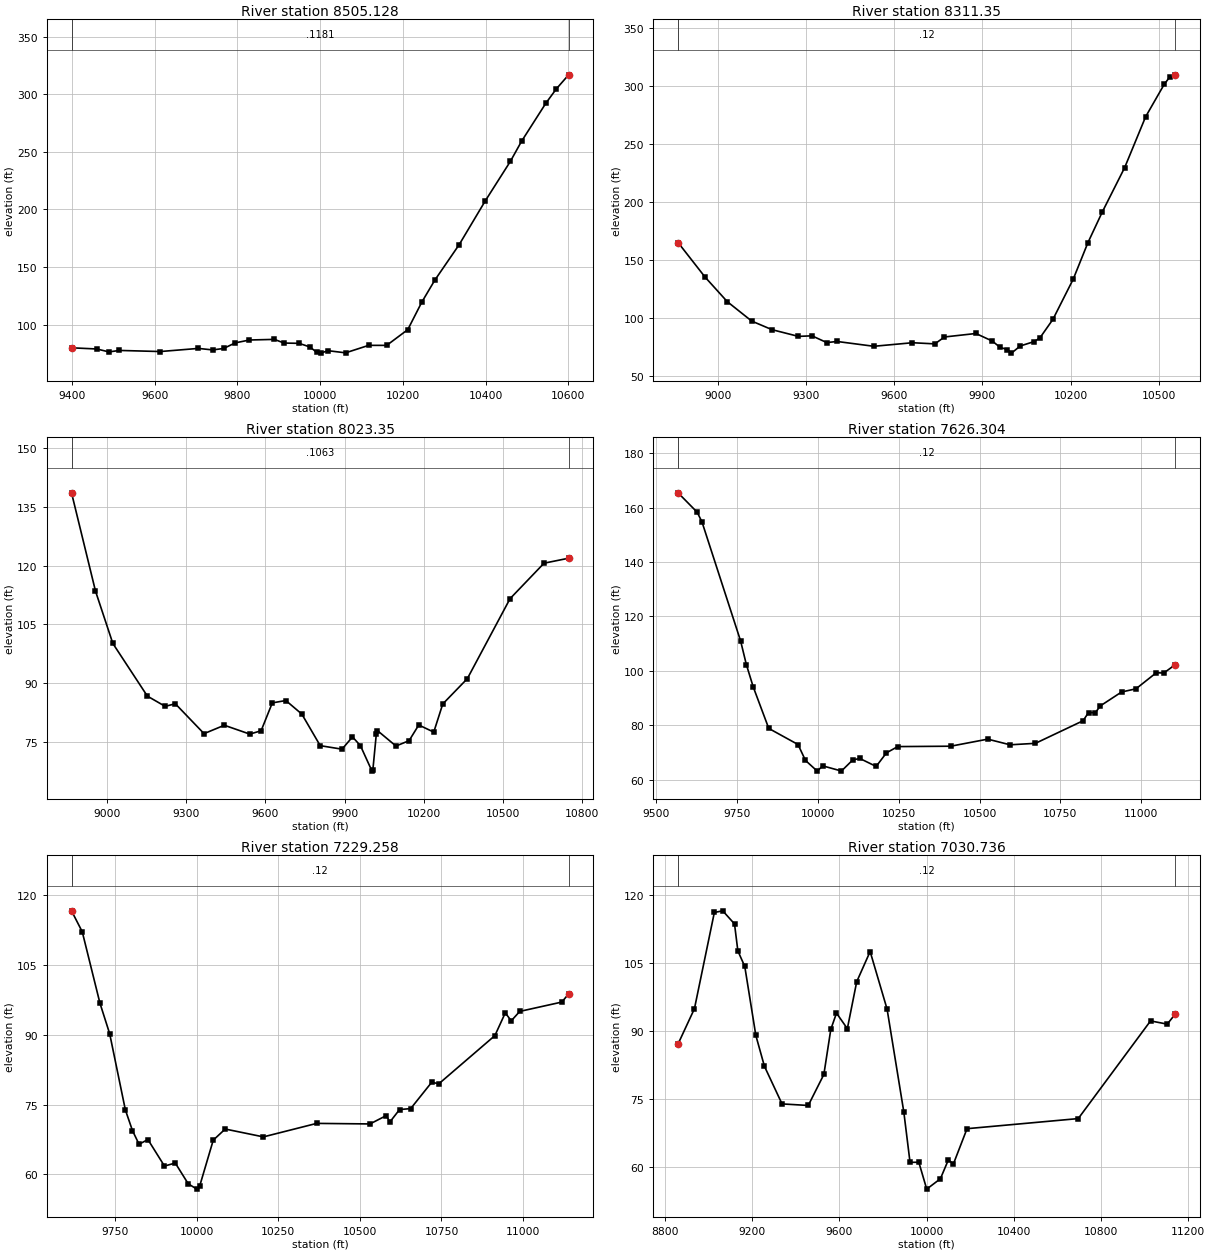
Type RM Length L Ch R = 1 ,8505.128,193.778900,193.778900,193.778900
XS GIS Cut Line= 6
1199773.71068151618814.3970934251199543.78153549619007.027008326
1199458.04008758619124.3076006571199436.77740174619203.135975325
1199435.60704056619443.6482791831199282.56383292619846.048552421
#Sta/Elev= 30
9399.13979.749649460.17978.71948 9489.6976.191259514.98577.457959613.67576.50336
9705.89979.218479740.21977.909069766.73679.159949794.87284.031889829.33986.53202
9889.58887.067429913.02183.86877 9949.23 83.63629975.66780.449479992.25475.67571
10002.2175.1186910018.7877.2623910061.6175.3753610117.6381.8827710161.0381.85193
10211.9795.5254210246.05119.537510277.17138.443110336.28169.439410399.77207.7281
10459.98241.7977 10487.1259.325610545.98292.485110571.16304.862410600.88 317.084
#Mann= 3 , 0 , 0
9399.139  0.1181       09399.139  0.1181       010600.88  0.1181       0
#XS Ineff= 2 , 0
       09836.228                       0
Bank Sta=9399.139,10600.88
Exp/Cntr=0.3,0.1

Type RM Length L Ch R = 1 , 8311.35,288.000000,288.000000,288.000000
XS GIS Cut Line= 6
 1200145.1154535618473.7046279381199852.24261662618732.418089597
1199499.64797231 619002.555051421199340.81205038619164.580093135
1199231.54533211619250.7448612411198941.27665855619643.063419923
#Sta/Elev= 30
8865.387165.14278957.129135.39149032.534114.24569115.62397.484729184.65690.06727
9274.68484.259579320.70484.754439370.90678.932319406.12379.876879531.07175.72966
9662.444 78.79819738.58377.808469771.28683.75382 9878.05 86.75759934.09980.20752
9959.817 74.88499984.30272.91928    999969.8363210028.9776.0044310076.9579.85182
 10095.882.9913310140.0198.9549710208.93 133.55910259.01165.076510308.06191.6177
 10383.9229.728710455.14273.532210518.46301.529710538.25308.168710555.62309.6831
#Mann= 3 , 0 , 0
8865.387    0.12       08865.387    0.12       010555.62    0.12       0
#XS Ineff= 2 , 0
       09808.397                       0
Bank Sta=8865.387,10555.62
Exp/Cntr=0.3,0.1

Type RM Length L Ch R = 1 , 8023.35,397.045500,397.045500,397.045500
XS GIS Cut Line= 6
1200080.29944769618499.0658801651199797.20023018 618734.34339729
1199549.40520006618890.4441634711198956.32637292619054.768845335
1198775.50407308619201.0177549871198525.15084928619475.532249957
#Sta/Elev= 30
8864.189138.58648955.067113.47839020.935100.07649151.99886.61012 9219.4983.99426
 9257.9684.662439366.95177.017299443.94579.163869540.54276.899859583.48777.76105
9625.87584.882879677.34685.483079737.85682.022789807.71673.943129890.42373.04686
9930.12376.181199960.17573.9500110004.1467.4342310007.5367.8266510020.36 76.8227
10024.6777.8051610094.9873.8510110144.7975.2173710181.5979.2298610238.4377.40825
10272.56 84.599710365.8891.0853710527.87111.527710656.85120.595910750.11121.8677
#Mann= 3 , 0 , 0
8864.189  0.1063       08864.189  0.1063       010750.11  0.1063       0
#XS Ineff= 2 , 0
       09658.658        10041.88       0
Bank Sta=8864.189,10750.11
Exp/Cntr=0.3,0.1

Type RM Length L Ch R = 1 ,7626.304,397.045600,397.045600,397.045600
XS GIS Cut Line= 6
1199642.73697888618509.6803144171199376.60287483618628.691724847
1199181.46199509618645.4306195771199070.10648984618737.586528131
1198629.58209857619185.1896360221198459.44320968619396.995191589
#Sta/Elev= 30
9568.165165.4481  9627.3158.30549642.115154.73789761.643110.89519779.265102.2678
9800.40794.091469848.46778.808659938.87672.887629961.93167.036669998.317 63.0975
10015.16 65.039810073.1263.13439   1010867.2029510129.7967.7597110180.4164.82505
10212.2269.8178310247.0472.1220210410.7572.2611810525.2474.8609610594.2972.78093
10672.6773.3195310819.8581.6208710836.7984.6418910857.75 84.587410873.4787.10688
 10938.892.1930110983.4893.3756811046.3599.2983611069.2599.1664511104.56102.2297
#Mann= 3 , 0 , 0
9568.165    0.12       09568.165    0.12       011104.56    0.12       0
#XS Ineff= 2 , 0
       0                10402.87       0
Bank Sta=9568.165,11104.56
Exp/Cntr=0.3,0.1

Type RM Length L Ch R = 1 ,7229.258,198.522700,198.522700,198.522700
XS GIS Cut Line= 6
1199079.92617601618256.3379173811198860.14947684  618648.2349095
1198785.07840987618821.4853224641198727.27895231618914.738274081
1198560.07305738619118.9585055761198208.14073797619489.538606128
#Sta/Elev= 30
9615.862116.58889648.773112.08549702.83496.80223  9732.990.186819780.877 73.8643
9802.69369.410269822.91766.471149849.96167.496469900.86561.794019933.89462.45157
9973.69857.9836610000.0856.84401 10008.457.4210610050.3467.3587710086.9969.74455
10204.0968.05936 10367.570.95676 10530.870.8378110581.1572.6439710591.3371.21539
10621.5973.93343 10655.574.1264710719.87 79.768210742.27 79.479510913.7189.80195
10945.6194.6830310963.8592.9746810989.9494.9968811118.8397.0020511139.7898.75104
#Mann= 3 , 0 , 0
9615.862    0.12       09615.862    0.12       011139.78    0.12       0
#XS Ineff= 2 , 0
       0                 10240.6       0
Bank Sta=9615.862,11139.78
Exp/Cntr=0.3,0.1

Type RM Length L Ch R = 1 ,7030.736,198.522800,198.522800,198.522800
XS GIS Cut Line= 6
 1199561.5364028617738.6042892341199141.74528791618005.303117061
1198797.82865151618318.609325771 1198740.5448515618432.583025589
1198698.60715508618867.4910461851198211.21308728619423.863163221
#Sta/Elev= 30
8859.89487.156088935.05294.93517 9026.33116.13179064.865116.49279118.813113.6042
9134.227107.65829165.919104.23669216.68989.030889256.04682.247089336.77973.95365
9457.08373.610429528.66780.440129560.49490.372429586.58793.956329636.41690.53715
9679.283100.86359740.914107.52759818.67994.833049895.37772.185019923.90461.08382
9964.24261.1019510000.4655.1784410063.2557.4678510099.6861.6223710122.8760.72174
10185.3968.4956210695.4670.7195511027.14  92.24311103.6491.5295911140.0693.71682
#Mann= 3 , 0 , 0
8859.894    0.12       08859.894    0.12       011140.06    0.12       0
#XS Ineff= 2 , 0
       0                10293.46       0
Bank Sta=8859.894,11140.06
Exp/Cntr=0.3,0.1

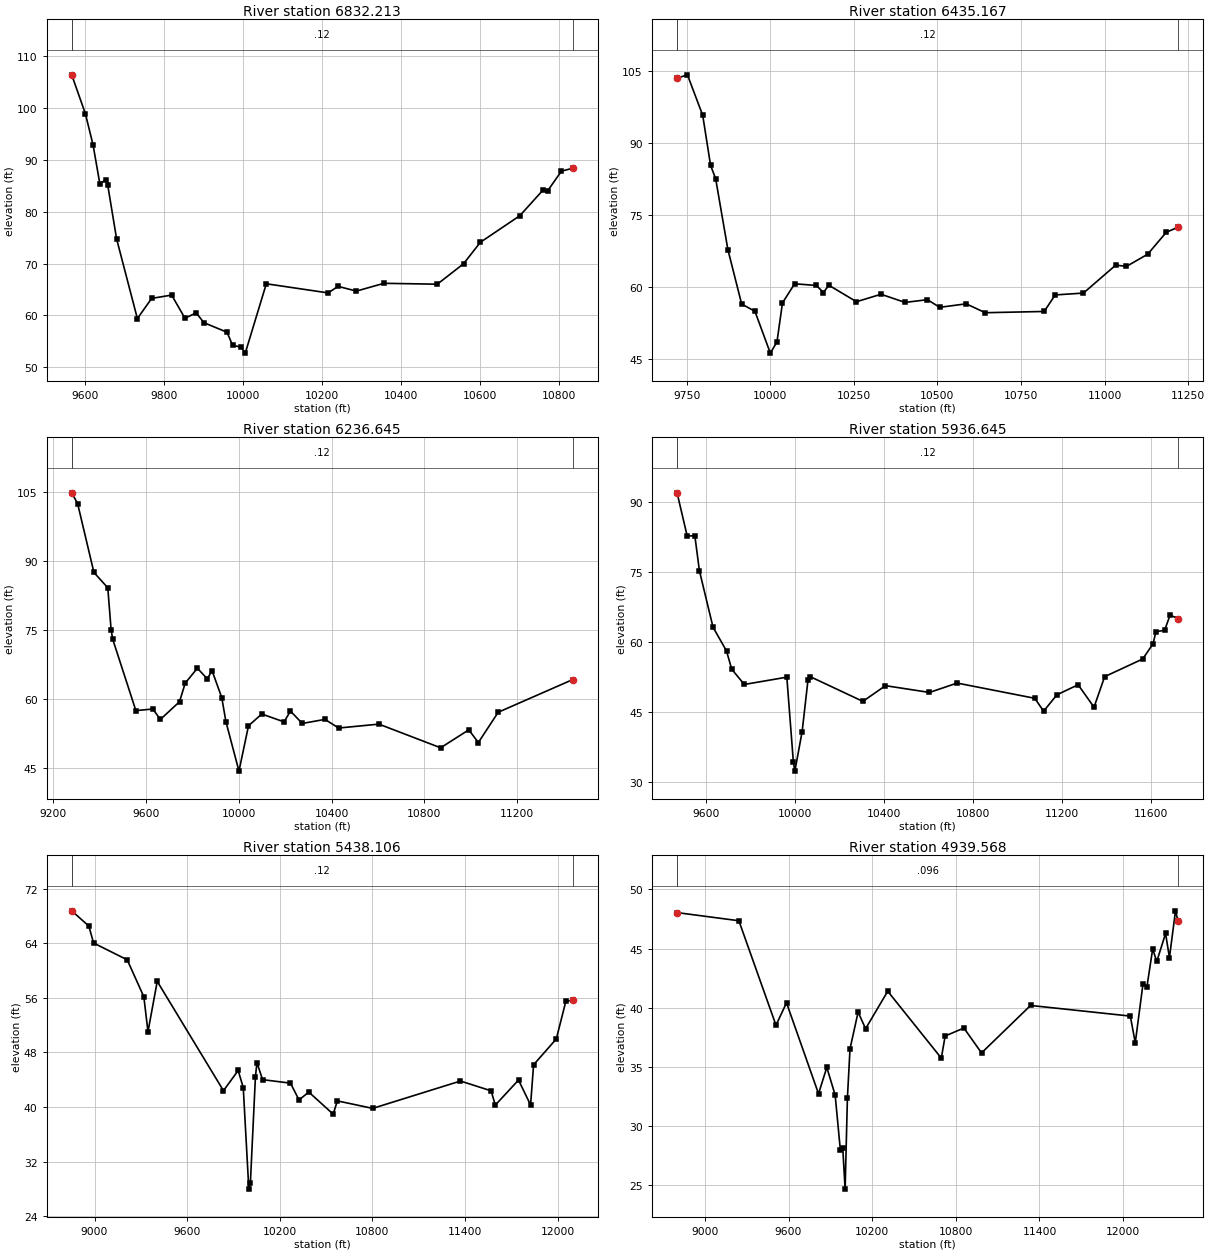
Type RM Length L Ch R = 1 ,6832.213,397.045500,397.045500,397.045500
XS GIS Cut Line= 6
1198813.46008193618258.2730208341198691.00701511 618414.70299311
1198593.93695635618566.9327813981198624.70316359618640.855194896
1198627.44544783618719.3084049671198237.22098744619337.967413798
#Sta/Elev= 30
9565.779106.32479600.59998.793479619.98892.78707 9637.0785.357429651.85386.10702
9656.979 85.14359679.51374.75033 9732.1959.402159768.49663.28405 9819.0863.92115
9852.84759.459469881.33760.500389900.79358.611119959.56656.764259973.571 54.2498
9995.39753.9023210005.6752.7456510059.0666.09817 10215.864.3388110240.9465.60057
10287.4964.6890110357.3166.1871410492.5466.0178110559.0169.9483510601.6874.08162
10701.6379.1986410760.7284.1520510772.3684.0048910807.2787.7885810835.9688.33466
#Mann= 3 , 0 , 0
9565.779    0.12       09565.779    0.12       010835.96    0.12       0
#XS Ineff= 2 , 0
       0                 10112.4       0
Bank Sta=9565.779,10835.96
Exp/Cntr=0.3,0.1

Type RM Length L Ch R = 1 ,6435.167,198.522800,198.522800,198.522800
XS GIS Cut Line= 6
1198824.25928978618208.9039621851198735.01674886618270.465683934
  1198651.392691618302.9669114121198448.08292796618291.504462315
1198319.81822601618389.0773949031197824.64812574619181.349555254
#Sta/Elev= 30
9721.486103.48319752.478104.17399798.17795.751129821.68285.333879836.88782.56258
9873.39767.835669914.63156.492169954.31554.9847810000.3646.2825410020.1848.61143
 10036.756.7351510073.0160.7056610138.1460.3621510158.9858.8894210175.4760.40296
10257.9156.9743110331.4358.5311410403.2356.8302310470.2857.4001410506.8555.80968
10586.0956.5393910642.8654.6909710819.3654.9491310852.0158.3892410936.58 58.7718
11033.4164.6068311064.8964.3081911128.7866.86034 11184.5 71.434111219.7372.47268
#Mann= 3 , 0 , 0
9721.486    0.12       09721.486    0.12       011219.73    0.12       0
#XS Ineff= 2 , 0
       0                10136.29       0
Bank Sta=9721.486,11219.73
Exp/Cntr=0.3,0.1

Type RM Length L Ch R = 1 ,6236.645,300.000000,300.000000,300.000000
XS GIS Cut Line= 6
1199213.93704918617817.6275949781198896.44265577617980.854070425
1198565.64842749618114.1046190861198386.90868539618148.535632148
1198220.78420594618197.8392872511197574.02654299619077.550747141
#Sta/Elev= 30
9279.237104.79889304.639102.45799375.00287.489349434.87484.148599449.06875.06772
9456.09472.963429556.05157.446339629.25157.802479661.65355.532779744.24659.38394
9768.78263.417589821.36466.67508 9864.3564.345049884.46266.163629926.66460.25893
9944.35755.0680710000.7444.29548 10041.854.1445610098.9256.71197 10195.455.00299
10222.7857.3410610274.1154.6597610371.8655.5451710430.8153.6651710604.4954.51355
10870.5949.3686510992.2153.2667911033.4850.5098411118.9957.0939211440.7864.20334
#Mann= 3 , 0 , 0
9279.237    0.12       09279.237    0.12       011440.78    0.12       0
#XS Ineff= 2 , 0
       09818.253        10151.51       0
Bank Sta=9279.237,11440.78
Exp/Cntr=0.3,0.1

Type RM Length L Ch R = 1 ,5936.645,498.538200,498.538200,498.538200
XS GIS Cut Line= 6
1199060.94401604 617725.642746971198726.30300814617807.066233739
1198498.17677706617822.6138542291198326.64815837617815.363071889
  1198009.056301 618170.519557581197424.72098747619021.995191574
#Sta/Elev= 30
9467.84591.904229513.38282.64451 9547.8182.698179568.36775.20632 9629.6163.09342
9690.30257.996589713.76154.085429770.42950.809449961.68852.375659991.25734.12746
9997.82832.2281410030.6740.7246910056.9451.7777610066.7952.4901810303.8347.18707
10405.5150.5535510603.56 49.100410727.9851.1108811077.3747.8467111117.1745.08216
11176.8548.5885311272.3550.7487511343.9745.9382211391.7252.4860211562.8256.26904
11609.3159.5068311622.5162.1431411661.4962.4167911686.1865.6856511722.3464.94259
#Mann= 3 , 0 , 0
9467.845    0.12       09467.845    0.12       011722.34    0.12       0
#XS Ineff= 2 , 0
       09821.464        10147.71       0
Bank Sta=9467.845,11722.34
Exp/Cntr=0.3,0.1

Type RM Length L Ch R = 1 ,5438.106,498.538300,498.538300,498.538300
XS GIS Cut Line= 6
1199680.19157523617149.3134863671199037.18266445617309.287495822
1198709.21064708617333.2788569931198384.55373231617317.634778753
1198152.48488179617473.8664510551197275.41543189618869.217413813
#Sta/Elev= 30
8852.30568.777938962.99366.549578994.086 64.0552 9211.9361.591119319.46256.17272
9346.309 51.0478 9406.2658.430239835.33542.399239930.55845.360429963.44642.85452
9999.62427.96195 10009.528.7959510042.4144.4512910052.2846.5267910088.4344.01835
10269.3943.5051710324.7641.0437810388.0442.1964910546.0638.9560810573.1840.90422
10801.8239.8033911370.6443.8153711569.0942.3796911596.2240.28484 11746.743.95892
11824.8540.3000211844.2246.1961411991.4849.9907912053.4855.5363612098.1355.65621
#Mann= 3 , 0 , 0
8852.305    0.12       08852.305    0.12       012098.13    0.12       0
#XS Ineff= 2 , 0
       09772.003        10143.02       0
Bank Sta=8852.305,12098.13
Exp/Cntr=0.3,0.1

Type RM Length L Ch R = 1 ,4939.568,706.873800,706.873800,706.873800
XS GIS Cut Line= 6
 1199625.0497815 616717.554177211199255.57608846616799.064138293
1199031.27608752616818.4349006411198620.22687554616816.829673171
1198417.68488494616855.0354489681197094.85987633618824.078524932
#Sta/Elev= 30
8800.43648.042459243.70647.354749509.98338.530779585.45340.424879815.15332.74363
9874.41434.97002 9934.3732.635089971.73727.977419988.77728.2035110005.82 24.6905
 10022.332.37722 10040.936.5345210098.9939.6397310152.6838.2387910311.5341.40076
10695.8135.7523310723.3637.6212710857.8638.2948810984.34 36.192711336.1140.20148
 12051.539.3031312087.0837.0458812142.4142.0178412170.6541.7724412211.84 44.9684
12241.2543.9146512304.4646.2835612332.1344.2385112375.6148.1921712394.4347.30221
#Mann= 3 , 0 , 0
8800.436   0.096       08800.436   0.096       012394.43   0.096       0
#XS Ineff= 2 , 0
       09558.965        10120.88       0
Bank Sta=8800.436,12394.43
Exp/Cntr=0.3,0.1

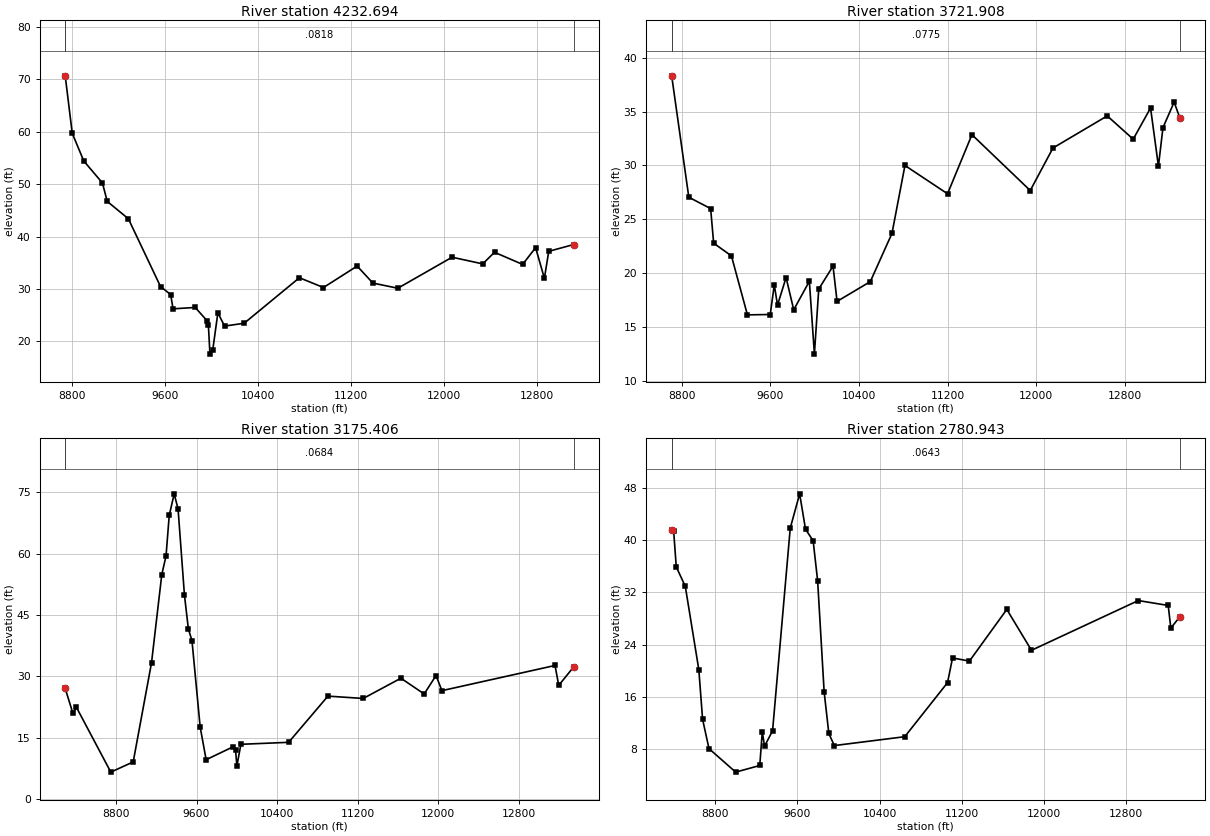
Type RM Length L Ch R = 1 ,4232.694,510.786200,510.786200,510.786200
XS GIS Cut Line= 6
1199830.30700108615731.7582023291199330.47498181616000.438971594
 1198464.7032727616287.6093007481198287.04507881616411.467651099
1198202.02635455616623.890262216 1196997.6376541618758.106302693
#Sta/Elev= 30
  8740.270.654918800.74759.702648900.04954.414999061.02350.213099102.00946.70359
9284.15943.390819560.93330.464449648.24828.939899669.07426.21486 9859.7126.47284
9962.85623.917079973.05823.142769986.68117.5718710010.54 18.323410054.8425.45437
10112.5822.9197510281.1923.4598810757.04 32.143110964.2430.2738111254.3134.36761
11389.9331.1230611604.6630.1394912071.7936.0567412335.4934.7850312437.2136.99392
12679.3834.6861512791.32 37.877812866.6732.0281412904.3437.1812313117.7738.47024
#Mann= 3 , 0 , 0
  8740.2  0.0818       0  8740.2  0.0818       013117.77  0.0818       0
#XS Ineff= 2 , 0
       0                10641.51       0
Bank Sta=8740.2,13117.77
Exp/Cntr=0.3,0.1

Type RM Length L Ch R = 1 ,3721.908,546.502300,546.502300,546.502300
XS GIS Cut Line= 6
 1199383.3508085614882.1403851511198734.05234501615551.602993563
1198364.11295608615850.8536413911198242.88583872616010.637625754
1198147.58078378616452.6163478341196942.08209857618671.300747156
#Sta/Elev= 30
8708.75338.313928863.43927.05685  9060.626.001919087.84622.794259248.36621.61645
9392.77916.14587 9598.7216.180649635.41818.92607 9664.4717.048759741.825 19.6098
9810.89316.618879952.10819.26204 9997.53 12.505810036.8518.5430810165.8120.66842
 10202.217.3962810502.5319.2314410698.2723.7064110815.2229.9996911199.8127.37559
 11420.132.8552111946.5827.6762312151.94 31.622312641.9734.59771 12876.332.43822
13033.1235.3309313104.0729.9345513145.1433.5072113245.9535.8745113298.9634.37105
#Mann= 3 , 0 , 0
8708.753  0.0775       08708.753  0.0775       013298.96  0.0775       0
#XS Ineff= 2 , 0
       09591.955        10821.57       0
Bank Sta=8708.753,13298.96
Exp/Cntr=0.3,0.1

Type RM Length L Ch R = 1 ,3175.406,394.462700,394.462700,394.462700
XS GIS Cut Line= 6
1198586.49220714 613933.670134471198095.37870061615205.337131277
1198032.17062241 615411.989158721197926.97742891615986.859573394
1197989.42004734616420.9844440221196896.94320965618605.328524917
#Sta/Elev= 30
8296.59327.059648373.31420.967198408.44922.443188749.2616.6412518971.4739.140656
9153.31533.342389255.20754.88094 9297.3759.422369329.01869.318539378.18174.58974
9416.82970.885519480.07349.868679519.06541.59046 9554.7238.764979635.97717.67401
9695.3039.6791489957.21712.752919987.18112.1479410000.478.12781410040.3713.43632
10514.1413.9176310904.22 25.197311254.3524.6263611628.5229.5691111859.6225.72319
11977.0130.22767 12035.726.53343 13158.2 32.681913194.8827.8166113341.9332.28881
#Mann= 3 , 0 , 0
8296.593  0.0684       08296.593  0.0684       013341.93  0.0684       0
#XS Ineff= 2 , 0
       09417.059        10455.98       0
Bank Sta=8296.593,13341.93
Exp/Cntr=0.3,0.1

Type RM Length L Ch R = 1 ,2780.943,986.156700,986.156700,986.156700
XS GIS Cut Line= 6
1198339.96442941613971.8645789031197667.83282977615332.403761506
1197590.66217193615551.0189664071197645.03766531616211.052638412
1197772.10151207616570.550351009 1196841.3876541618515.050747156
#Sta/Elev= 30
  8376.441.630688395.423 41.44518421.05935.910858508.95532.922488640.79920.15252
8677.42312.553788739.6838.0643688999.7094.4663239234.0985.4823959258.42110.64856
9280.569 8.442949358.61810.787249530.74841.842579622.30647.09747 9679.2841.68079
9753.71739.904589797.41833.772969860.70216.782339906.40310.383649959.8428.534881
10645.649.89206211062.0418.1721711110.7521.9562311275.4121.4770811639.1429.39177
 11879.223.1302812919.4630.7483213210.4429.99817 13235.926.5290113325.2828.29566
#Mann= 3 , 0 , 0
  8376.4  0.0643       0  8376.4  0.0643       013325.28  0.0643       0
#XS Ineff= 2 , 0
       0 9615.61        10446.12       0
Bank Sta=8376.4,13325.28
Exp/Cntr=0.3,0.1