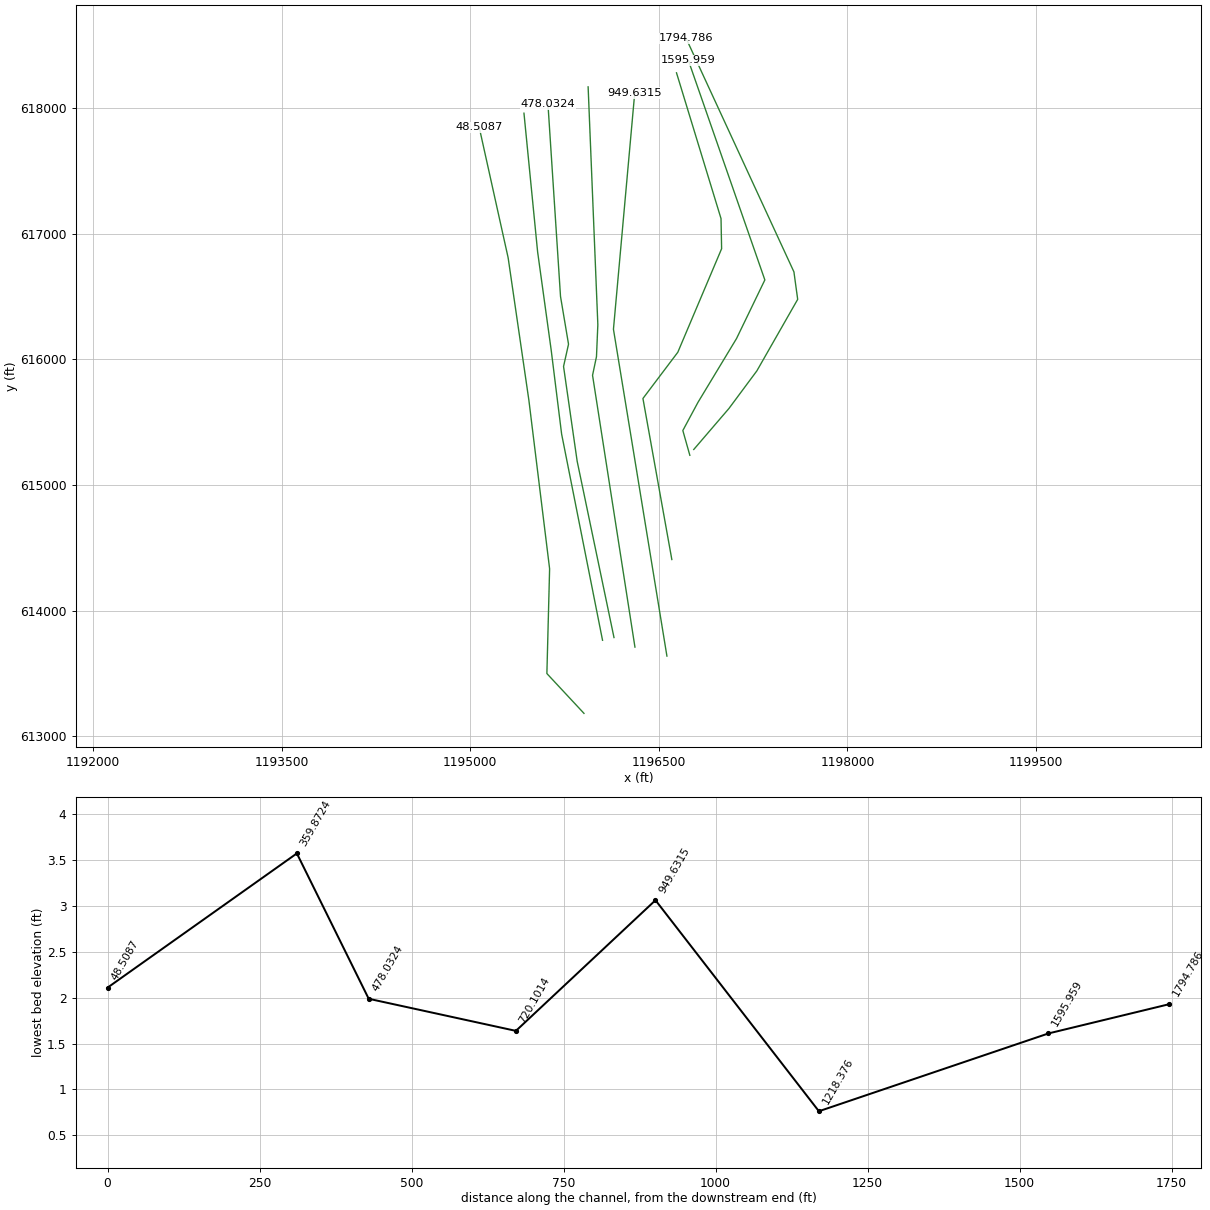
HEC-RAS study 128_ras.prj: 128

--- 128_ras.g01 (geometry) --- (continued)

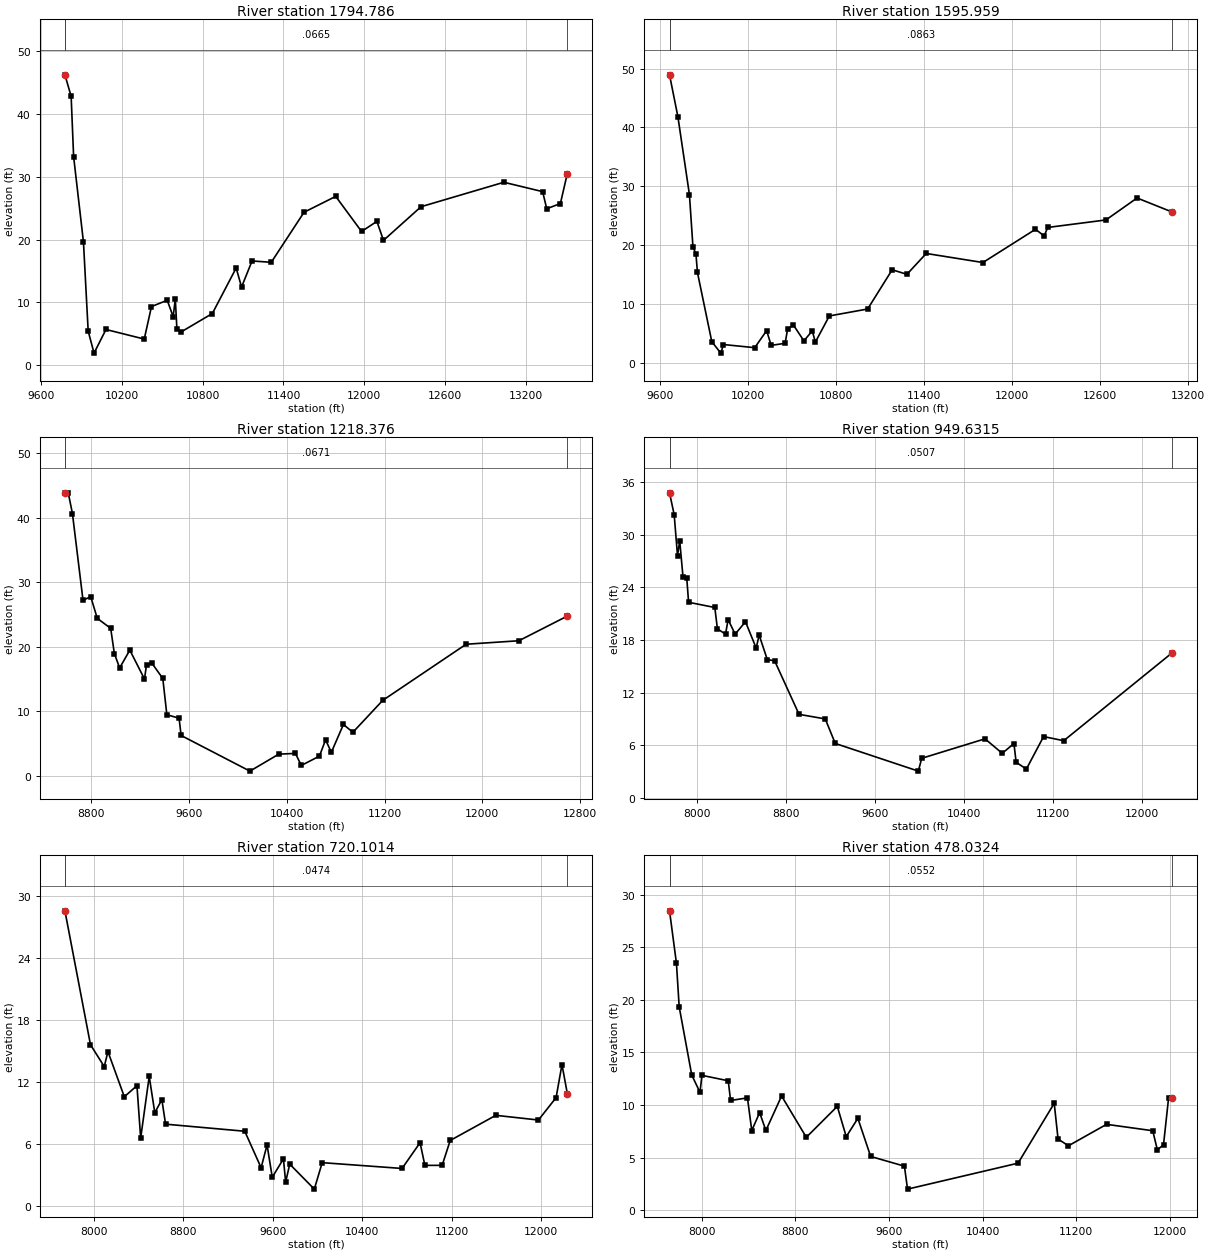
Type RM Length L Ch R = 1 ,1794.786,198.827300,198.827300,198.827300
XS GIS Cut Line= 6
1196777.24820212615282.6061358751197057.16577539 615608.88479802
1197279.24255285615907.9686226551197604.02023453616476.837294132
1197574.02654299616695.606302693 1196716.3876541618553.245191589
#Sta/Elev= 30
9779.57346.274899825.76342.85007  9844.133.245179917.16119.607589951.979  5.4567
9995.502 1.9309110083.98 5.6969210367.844.16981510421.349.34875710538.0810.35404
10582.367.73826810598.07 10.587610609.865.79839910640.775.30318110872.728.242607
 11049.315.4968111089.3512.4649811167.1516.6172611309.5516.4031411552.6124.37717
11787.4126.9044211978.9321.3169312092.68 22.920312141.5419.8952812419.7925.25738
 13034.129.1543413321.5327.66314 13352.124.9354713453.2825.7677113504.6430.54298
#Mann= 3 , 0 , 0
9779.573  0.0665       09779.573  0.0665       013504.64  0.0665       0
#XS Ineff= 2 , 0
       0                10365.88       0
Bank Sta=9779.573,13504.64
Exp/Cntr=0.3,0.1

Type RM Length L Ch R = 1 ,1595.959,377.582800,377.582800,377.582800
XS GIS Cut Line= 6
1196746.04450062615236.3445266191196690.36751029615433.460238487
 1196810.2357696615656.5923278781197117.52520087616165.159125537
 1197342.8209621616631.3794881251196733.74876523 618379.63408047
#Sta/Elev= 30
9666.99248.930189724.19841.78465 9802.6128.555169826.47419.689039846.92918.45393
9857.15715.325389954.9323.55909510016.081.61132810034.483.07189410247.422.537974
10328.455.43885810359.312.930205 10454.33.280231 10471.25.71704410510.546.401149
10582.223.69474810639.025.39322610660.383.486624 10755.47.933195 11016.49.114777
11183.3315.7805511284.03 15.015711415.4418.5559211801.3717.0152412159.49 22.6651
 12218.621.5418512242.9422.97891 12639.324.2542712851.3927.9898213088.8525.61509
#Mann= 3 , 0 , 0
9666.992  0.0863       09666.992  0.0863       013088.85  0.0863       0
#XS Ineff= 2 , 0
       0                10447.86       0
Bank Sta=9666.992,13088.85
Exp/Cntr=0.3,0.1

Type RM Length L Ch R = 1 ,1218.376,268.744800,268.744800,268.744800
XS GIS Cut Line= 6
1196602.81533399614407.3514710661196372.95282537615688.339390635
1196650.39020854616056.0522612481196998.84441221616879.625489026
1196994.16543192617119.2174137981196639.99876523618278.939636037
#Sta/Elev= 30
8582.88343.851998611.07443.760938644.40640.64973 8731.0727.220948794.40227.76701
8847.73324.42136 8957.7322.868348987.72918.969539031.06116.735719114.39219.50129
9234.38915.023299251.05517.231239294.38717.495959384.384 15.11169417.7179.489424
9517.7148.960471 9534.38  6.282710097.970.76247810334.083.39214810470.823.506424
10518.221.63711110666.883.08350510717.315.59790210764.73  3.679710863.367.983921
10941.066.77692411185.4211.7162211868.0720.40764 12300.320.9501812696.87 24.7695
#Mann= 3 , 0 , 0
8582.883  0.0671       08582.883  0.0671       012696.87  0.0671       0
#XS Ineff= 2 , 0
       09629.934        10529.08       0
Bank Sta=8582.883,12696.87
Exp/Cntr=0.3,0.1

Type RM Length L Ch R = 1 ,949.6315,229.530100,229.530100,229.530100
XS GIS Cut Line= 4
1196563.75283396613639.1223043951196272.95422289 615418.63619332
1196138.40561178 616238.94869329 1196307.6764451618118.288971066
#Sta/Elev= 30
7751.33334.784217793.26832.286247823.18727.629767843.13329.306667873.05225.13425
7906.29625.085117922.91722.309578158.94621.714568182.21719.280958255.35318.67918
8278.62320.334258341.78618.674888434.867  20.0918531.27417.087238557.86818.57504
8631.00415.782728697.49115.634278916.8989.5372269152.9279.0141299242.6856.219406
9990.7063.06466910020.634.52641910590.576.74643510745.395.09469210850.816.210724
10870.574.07255310962.813.30040811117.637.00396911298.816.53054712272.67 16.5303
#Mann= 3 , 0 , 0
7751.333  0.0507       07751.333  0.0507       012272.67  0.0507       0
#XS Ineff= 2 , 0
       09613.278        10697.72       0
Bank Sta=7751.333,12272.67
Exp/Cntr=0.3,0.1

Type RM Length L Ch R = 1 ,720.1014,242.069000,242.069000,242.069000
XS GIS Cut Line= 5
1196309.37647748613710.7497729811195972.15186712615872.682287589
1196003.42248356616021.2177155461196014.23758858616275.853939682
1195936.97242364618167.163766935
#Sta/Elev= 30
7744.41828.57344 7972.8115.616048095.66813.499138128.873 14.94568274.97610.58152
8387.87311.647588421.0786.574487 8497.4512.549798547.2579.0319788610.34710.30327
8643.5527.925848 9350.827.2418199496.9223.708119 9550.055.9195279596.5372.784466
9696.1524.5703889716.075 2.326639752.6014.0575559972.1361.63921110042.544.201685
10755.963.63931410916.856.13720410959.543.93791811113.873.939773 11186.16.349319
11593.278.78140711974.168.32652112131.7710.4966612184.3113.6950912232.0410.87878
#Mann= 3 , 0 , 0
7744.418  0.0474       07744.418  0.0474       012232.04  0.0474       0
#XS Ineff= 2 , 0
       09592.354         10682.7       0
Bank Sta=7744.418,12232.04
Exp/Cntr=0.3,0.1

Type RM Length L Ch R = 1 ,478.0324,118.160000,118.160000,118.160000
XS GIS Cut Line= 6
1196142.74588951613786.6917488431195849.81455487615188.872053802
1195741.47038659615942.8171800941195781.04814923616120.437880997
1195717.39866734616499.3653599471195617.57227841618027.143137723
#Sta/Elev= 30
7725.92528.481847785.03223.483427808.49419.342377915.74712.849057986.13211.20316
 8002.89 12.82048227.45112.303568247.56110.427058391.68310.676318428.5517.563389
8495.5859.2724118549.2117.5748498683.27810.853438894.4326.9222539159.205 9.86804
9235.4396.9831219334.8758.7275199444.2555.1001479732.6194.1737789759.1351.989417
10703.194.45953211012.2410.1594211045.126.75390611133.896.11669811459.398.157131
11853.937.54763411893.38 5.7221911945.996.21672211988.7310.6214412017.85 10.6464
#Mann= 3 , 0 , 0
7725.925  0.0552       07725.925  0.0552       012017.85  0.0552       0
#XS Ineff= 2 , 0
       09568.769        10500.91       0
Bank Sta=7725.925,12017.85
Exp/Cntr=0.3,0.1

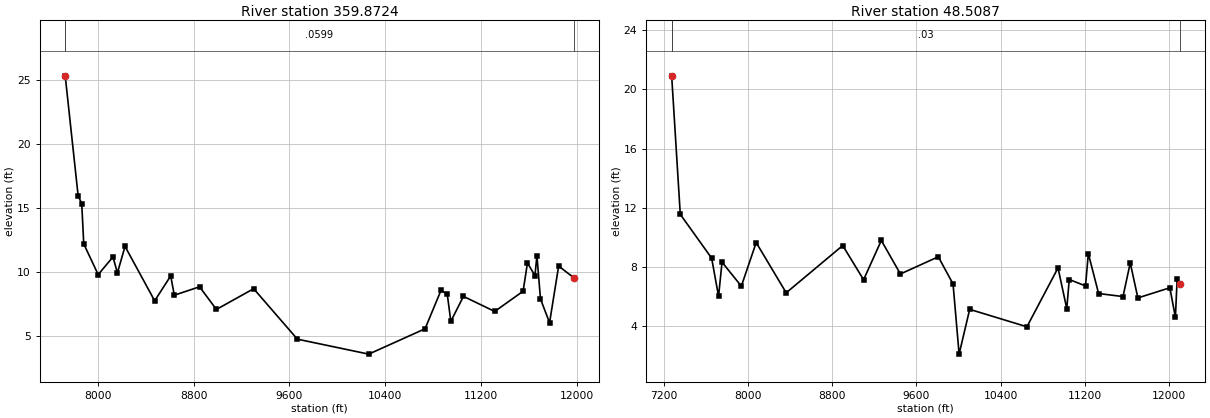
Type RM Length L Ch R = 1 ,359.8724,311.363700,311.363700,311.363700
XS GIS Cut Line= 5
 1196051.6000562613764.9903599621195726.07922286615405.615359947
1195643.61394507616069.6778599621195535.10700062616855.268137723
1195426.60005623617957.698693305
#Sta/Elev= 30
7728.08725.339847835.95515.962877866.05815.342587882.78212.197648003.195  9.7962
8126.95211.175758163.7459.9219258227.29612.00087 8474.817.7449248608.6029.693828
8638.7058.1844968849.4268.8411548989.9087.0694659300.9738.6911149665.7924.745417
10261.223.57536710731.525.558439   10864 8.5524910916.748.27345910946.416.133605
11051.918.09400811312.356.91305111549.718.49311511585.9710.7011211648.619.718542
11665.0911.2720611694.767.89567311770.596.02931711846.4110.4652411970.669.564752
#Mann= 3 , 0 , 0
7728.087  0.0599       07728.087  0.0599       011970.66  0.0599       0
#XS Ineff= 2 , 0
       09614.818        10456.24       0
Bank Sta=7728.087,11970.66
Exp/Cntr=0.3,0.1

Type RM Length L Ch R = 1 , 48.5087,0.000000,0.000000,0.000000
XS GIS Cut Line= 6
1195904.03061178613183.3931377381195608.89172289613500.233415514
1195630.59311175614333.566748857 1195465.6625562615674.712582186
1195300.73200062616807.5250821861195070.69727841617844.851471066
#Sta/Elev= 30
7272.03220.913597353.84911.55508 7652.288.5944027717.9946.0114467750.8148.324359
7934.6036.7026928075.7269.6473778361.2566.2548568898.7849.4475139097.1177.136631
  9265.79.7906429447.5057.525375 9807.818.6883819948.0416.84904810005.62 2.11071
10106.055.13634910650.563.95852510946.387.93691511029.485.179102   110537.152312
 11207.76.71895811234.618.90317511332.17 6.20442 11564.36.00071211633.198.276473
11705.575.90764712010.026.59449212062.614.59008912079.047.19744512106.316.834812
#Mann= 3 , 0 , 0
7272.032    0.03       07272.032    0.03       012106.31    0.03       0
#XS Ineff= 2 , 0
       09892.223        10570.89       0
Bank Sta=7272.032,12106.31
Exp/Cntr=0.3,0.1